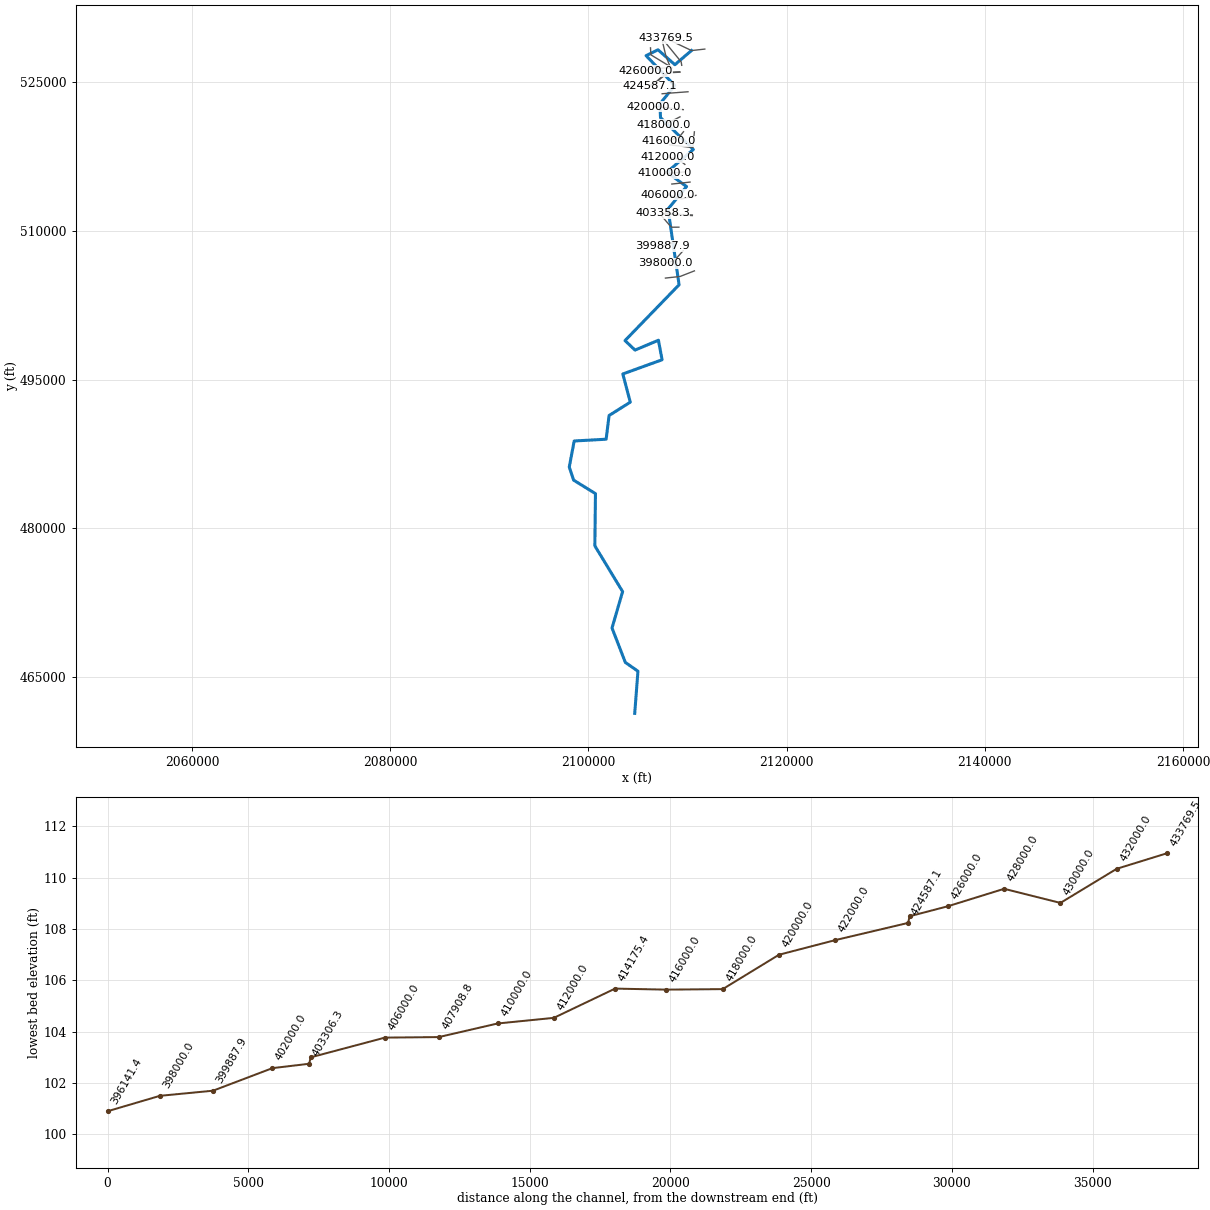
--- B4950SOUTHRIVERS.prj (project) ---

Proj Title=B4950 SOUTH RIVER SR1851
Current Plan=p03
Default Exp/Contr=0.3,0.1
English Units
Geom File=g01
Geom File=g02
Geom File=g03
Flow File=f02
Flow File=f03
Plan File=p01
Plan File=p02
Plan File=p03
Y Axis Title=Elevation
X Axis Title(PF)=Main Channel Distance
X Axis Title(XS)=Station
BEGIN DESCRIPTION:
####(Watershed Name)####
SOUTH RIVER
HCFCD Unit X###-##-##
(Flood Hazard, Floodway) Model
10, 2, 1, 0.2% Event
Filename:  N:\NC_flood\60273\Approximates\Eng\South_River\Eng\South River.prj
Prepared by:  ________     Date: ________
Reviewed by:  ________     Date: ________
STATUS (Draft RAS, SVSQ, FINAL)
END DESCRIPTION:
DSS Export Rating Curves= 0
DSS Export Rating Curve Sorted= 0
DSS Export Volume Flow Curves= 0
DXF Filename=..\SOUTH RIVER_UPPER.
DXF OffsetX= 0
DXF OffsetY= 0
DXF ScaleX= 1
DXF ScaleY= 10

--- B4950SOUTHRIVERS.p03 (plan) ---

Plan Title=Revised
Program Version=4.10
Short Identifier=Revised
Geom File=g03
Flow File=f03
Subcritical Flow
K Sum by GR= 0
Std Step Tol= 0.01
Critical Tol= 0.01
Num of Std Step Trials= 20
Max Error Tol= 0.3
Flow Tol Ratio= 0.001
Split Flow NTrial= 30
Split Flow Tol= 0.02
Split Flow Ratio= 0.02
Log Output Level= 0
Friction Slope Method= 1
Unsteady Friction Slope Method= 2
Unsteady Bridges Friction Slope Method= 1
Parabolic Critical Depth
Global Vel Dist= 0 , 0 , 0
Global Log Level= 0
CheckData=True
Encroach Param=-1 ,0,0, 2
Encroach River=South River
Encroach Reach=Reach - 1
Encroach Node=433769.5
       1 4845.78 6114.18
Encroach Node=432000.0
       1  4956.2 5524.89
Encroach Node=430000.0
       1 4907.43 5412.11
Encroach Node=428000.0
       1 4451.19  5270.8
Encroach Node=426000.0
       1 4629.32 5139.98
Encroach Node=424642.1
       1  4874.5  5125.5
Encroach Node=424587.1
       1  4874.5  5125.5
Encroach Node=422000.0
       1 3983.83 5234.78
Encroach Node=420000.0
       1 3649.99  5044.4
Encroach Node=418000.0
       1 4357.57 5069.48
Encroach Node=416000.0
       1 4874.67 5900.39
Encroach Node=414175.4
       1 4152.85 5408.36
Encroach Node=412000.0
       1 4756.24 5278.99
Encroach Node=410000.0
       1 4335.56  5047.2
Encroach Node=407908.8
       1 4721.85 5684.49
Encroach Node=406000.0
       1 4027.96 5171.64
Encroach Node=403358.3
       1    4947    5053
Encroach Node=403306.3
       1    4947    5053
Encroach Node=402000.0
       1 4604.88  5833.7
Encroach Node=399887.9
       1 4829.53 5245.26
Encroach Node=398000.0
       1 4768.46 5317.58
Encroach Node=396141.4
       1 4672.22 5180.17
Encroach Node=394000.0
       1 4327.81 5239.69
Encroach Node=392000.0
       1 4511.37 5645.05
Encroach Node=390469.3
       1    4907    5093
Encroach Node=390421.3
       1    4907    5093
Encroach Node=388000.0
       1    4700    5300
Encroach Node=386000.0
       1 4581.47 5163.19
Encroach Node=384000.0
       1 4825.03 5110.51
Encroach Node=382000.0
       1 4775.87 5599.38
Encroach Node=380000.0
       1 4645.15 5324.94
Encroach Node=378000.0
       1 4741.28 5242.44
Encroach Node=376000.0
       1 4905.85 5679.54
Encroach Node=374000.0
       1 4750.85 5555.53
Encroach Node=372000.0
       1 4682.24 5214.19
Encroach Node=370000.0
       1  4719.3 5133.66
Encroach Node=368000.0
       1 4466.61 5256.97
Encroach Node=366000.0
       1  4947.9 5351.87
Encroach Node=363398.7
       1 4762.87 5406.45
Encroach Node=361148.9
       1  4947.5  5052.5
Encroach Node=361098.9
       1  4947.5  5052.5
Encroach Node=358173.1
       1 4576.92 5673.29
Encroach Node=356000.0
       1 4415.23  5052.7
Encroach Node=353798.3
       1 3764.06 5218.17
Encroach Node=352000.0
       1 4119.98 5184.89
Encroach Node=350000.0
       1  4659.2 5390.21
Encroach Node=348000.0
       1 4231.48 5187.71
Encroach Node=346629.3
       1    4820    5635
Encroach Node=346534
       1    4934 5536.77
Encroach Node=346437.
       1 4941.17 5553.17
Encroach Node=346295
       1    4855 5496.35
Encroach Node=344000.0
       1    3700    5800
Encroach Node=342000.0
       1    3700    5800
Encroach Node=340000.0
       1    3700    5800
Encroach Node=338000.0
       1    4300    6200
Encroach Node=336000.0
       1    4400    6650
Encroach Node=333813.5
       1 4423.19 6160.16
Encroach Node=332000.0
       1    4468    6785
Encroach Node=330276.7
       1    4668    5331
Computation Interval=1HOUR
Output Interval=1HOUR
Run HTab= 0
Run UNet= 0
Run PostProcess= 0
Run WQNet= 0
UNET Theta= 1
UNET Theta Warmup= 1
UNET ZTol= 0.02
UNET ZSATol= 0.05
UNET MxIter= 20
UNET MaxInSteps= 1
UNET DtIC= 0
UNET DtMin= 0
UNET MaxCRTS= 20
UNET WFStab= 2
UNET SFStab= 1
UNET WFX= 1
UNET SFX= 1
UNET DSS MLevel= 4
UNET DZMax Abort= 100
UNET Convert EG Bridges= 0
UNET Use Existing IB Tables=-1
UNET Froude Reduction=False
UNET Froude Limit= 1
UNET Froude Power= 10
UNET Time Slicing=0,0, 5
UNET Junction Losses=0
Instantaneous Interval=1HOUR
Write IC File= 0
Write IC File at Sim End=0
Echo Input=False
Echo Parameters=False
Echo Output=False
Write Detailed= 0
WQ AD Non Conservative
WQ ULTIMATE=-1
WQ Max Comp Step=1HOUR
WQ Output Interval=15MIN
WQ Output Selected Increments= 0
WQ Output face flow=0
WQ Output face velocity=0
WQ Output face area=0
WQ Output face dispersion=0
WQ Output cell volume=0
WQ Output cell surface area=0
WQ Output cell continuity=0
WQ Output cumulative cell continuity=0
WQ Output face conc=0
WQ Output face dconc_dx=0
WQ Output face courant=0
WQ Output face peclet=0
WQ Output face adv mass=0
WQ Output face disp mass=0
WQ Output cell mass=0
WQ Output cell source sink temp=0
WQ Output cell source sink nsm=0
WQ Output MaxMinRange=-1
WQ Daily Max Min Mean=-1
WQ Daily Range=0
WQ Daily Time=0
WQ Create Restart=0
WQ Fixed Restart=0
WQ System Summary=0
WQ Use Fixed Temperature=0
Sorting and Armoring Iterations= 10
XS Update Threshold= 0.02
Hydraulics Update Threshold= 0.02
Energy Slope Method= 1
Volume Change Method= 0
XS Weighting Method= 0
Number of US Weighted Cross Sections= 1
Number of DS Weighted Cross Sections= 1
Upstream XS Weight=0.25
Main XS Weight=0.5
Downstream XS Weight=0.25
Number of DS XS's Weighted with US Boundary= 1
Upstream Boundary Weight= 1
Weight of XSs Associated with US Boundary= 0
Number of US XS's Weighted with DS Boundary= 1
Downstream Boundary Weight= 0.5
Weight of XSs Associated with DS Boundary= 0.5
Sediment Output Level= 4
Mass or Volume Output= 0
Output Increment Type= 1
Profile and TS Output Increment= 10
XS Output Flag= 0
XS Output Increment= 10
Disregard all LS=0
Disregard all Conn=0
Disregard all Breaches=0
Disregard all Pumps=0

--- B4950SOUTHRIVERS.p01 (plan) ---

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Plan Title=Duplicate Effective
Short Identifier=Duplicate
Geom File=g01
Flow File=f02
Encroach Node=424614.6
Encroach Node=403332.3
Encroach Node=390445.3
Encroach Node=361123.9
Encroach Node=346503.7
       1  4927.5  5072.5
Encroach Node=346480.7
       1    4500    6000
Encroach Node=346457.7
       1    4700    5800
UNET Convert EG Bridges=-1

--- B4950SOUTHRIVERS.p02 (plan) ---

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Plan Title=Corrected Effective
Short Identifier=Corrected
Geom File=g02
Flow File=f03
       1  4829.1  5627.1
       1    4934 5522.77
       1 4961.17 5539.17
       1    4855 5481.35

--- B4950SOUTHRIVERS.f03 (steady flow) ---

Flow Title=Floodway
Program Version=4.10
Number of Profiles= 2
Profile Names=100yr,100yr_FW
River Rch & RM=South River,Reach - 1       ,433769.5
    5414    5414
River Rch & RM=South River,Reach - 1       ,432000
    5422    5422
River Rch & RM=South River,Reach - 1       ,426000
    5473    5473
River Rch & RM=South River,Reach - 1       ,422000
    5490    5490
River Rch & RM=South River,Reach - 1       ,418000
    5510    5510
River Rch & RM=South River,Reach - 1       ,412000
    5782    5782
River Rch & RM=South River,Reach - 1       ,410000
    5798    5798
River Rch & RM=South River,Reach - 1       ,406000
    5813    5813
River Rch & RM=South River,Reach - 1       ,403358.3
    5818    5818
River Rch & RM=South River,Reach - 1       ,399887.9
    5901    5901
River Rch & RM=South River,Reach - 1       ,396141.4
    5935    5935
River Rch & RM=South River,Reach - 1       ,394000
    5938    5938
River Rch & RM=South River,Reach - 1       ,390469.3
    5968    5968
River Rch & RM=South River,Reach - 1       ,382000
    5981    5981
River Rch & RM=South River,Reach - 1       ,376000
    6076    6076
River Rch & RM=South River,Reach - 1       ,372000
    6257    6257
River Rch & RM=South River,Reach - 1       ,366000
    6264    6264
River Rch & RM=South River,Reach - 1       ,363398.7
    6277    6277
River Rch & RM=South River,Reach - 1       ,361148.9
    6313    6313
River Rch & RM=South River,Reach - 1       ,353798.3
    6336    6336
River Rch & RM=South River,Reach - 1       ,352000
    6356    6356
River Rch & RM=South River,Reach - 1       ,350000
    6364    6364
River Rch & RM=South River,Reach - 1       ,348000
    6372    6372
River Rch & RM=South River,Reach - 1       ,346534
    6410    6410
River Rch & RM=South River,Reach - 1       ,340000
    6421    6421
River Rch & RM=South River,Reach - 1       ,338000
    6426    6426
River Rch & RM=South River,Reach - 1       ,336000
    6673    6673
River Rch & RM=South River,Reach - 1       ,332000
    6715    6715
Boundary for River Rch & Prof#=South River,Reach - 1       , 1
Up Type= 0
Dn Type= 1
Dn Known WS=101.7
Boundary for River Rch & Prof#=South River,Reach - 1       , 2
Up Type= 0
Dn Type= 1
Dn Known WS=102.67
DSS Import GetInterval= 0
DSS Import GetPeak= 0
DSS Import FillOption= 0

--- B4950SOUTHRIVERS.f02 (steady flow) ---

Flow Title=100-Year-Single Effective
Program Version=4.10
Number of Profiles= 2
Profile Names=100-Year,100-FW
River Rch & RM=South River,Reach - 1       ,433769.5
    5414    5414
River Rch & RM=South River,Reach - 1       ,432000
    5422    5422
River Rch & RM=South River,Reach - 1       ,426000
    5473    5473
River Rch & RM=South River,Reach - 1       ,422000
    5490    5490
River Rch & RM=South River,Reach - 1       ,418000
    5510    5510
River Rch & RM=South River,Reach - 1       ,412000
    5782    5782
River Rch & RM=South River,Reach - 1       ,410000
    5798    5798
River Rch & RM=South River,Reach - 1       ,406000
    5813    5813
River Rch & RM=South River,Reach - 1       ,403358.3
    5818    5818
River Rch & RM=South River,Reach - 1       ,399887.9
    5901    5901
River Rch & RM=South River,Reach - 1       ,396141.4
    5935    5935
River Rch & RM=South River,Reach - 1       ,394000
    5938    5938
River Rch & RM=South River,Reach - 1       ,390469.3
    5968    5968
River Rch & RM=South River,Reach - 1       ,382000
    5981    5981
River Rch & RM=South River,Reach - 1       ,376000
    6076    6076
River Rch & RM=South River,Reach - 1       ,372000
    6257    6257
River Rch & RM=South River,Reach - 1       ,366000
    6264    6264
River Rch & RM=South River,Reach - 1       ,363398.7
    6277    6277
River Rch & RM=South River,Reach - 1       ,361148.9
    6313    6313
River Rch & RM=South River,Reach - 1       ,353798.3
    6336    6336
River Rch & RM=South River,Reach - 1       ,352000
    6356    6356
River Rch & RM=South River,Reach - 1       ,350000
    6364    6364
River Rch & RM=South River,Reach - 1       ,348000
    6372    6372
River Rch & RM=South River,Reach - 1       ,346503.7
    6410    6410
River Rch & RM=South River,Reach - 1       ,340000
    6421    6421
River Rch & RM=South River,Reach - 1       ,338000
    6426    6426
River Rch & RM=South River,Reach - 1       ,336000
    6673    6673
River Rch & RM=South River,Reach - 1       ,332000
    6715    6715
Boundary for River Rch & Prof#=South River,Reach - 1       , 1
Up Type= 0
Dn Type= 1
Dn Known WS=101.7
Boundary for River Rch & Prof#=South River,Reach - 1       , 2
Up Type= 0
Dn Type= 1
Dn Known WS=102.67
DSS Import GetInterval= 0
DSS Import GetPeak= 0
DSS Import FillOption= 0

--- B4950SOUTHRIVERS.g03 (geometry) ---

Geom Title=Revised
Program Version=4.10

River Reach=South River     ,Reach - 1
Reach XY= 30
2110399.79402043528223.1223195332108726.36706412526790.777806034
2107022.34979784528294.2930406832105816.08757517527707.407093952
2108708.36688173524694.4965650732107209.60169521 522825.10762314
 2107278.0923892521442.0636091882110587.88592631 518239.16115518
2107924.10893509515937.2878310182109900.87896508514493.153198054
2108034.61005476512227.9102450562109149.37135029504581.802769443
2103692.56605819498948.0556844472104699.57626191 497989.10596771
2107066.84024865 498984.146050142107431.85394722497012.126068279
2103471.56381884495579.711554071 2104223.5714387492734.552724967
2102085.29977226491386.1990625212101788.54676536488995.274836035
2098562.26407444488817.5230349312098066.75905365486186.826378906
2098504.76349181484864.6929821422100709.53583208  483502.8091826
2100649.04521914478231.2557675992103450.56360605473614.798990488
2102381.30277157469940.791762923 2103727.3164103466464.976543576
2104997.32927895 465581.497591562104671.32597566461326.024472183

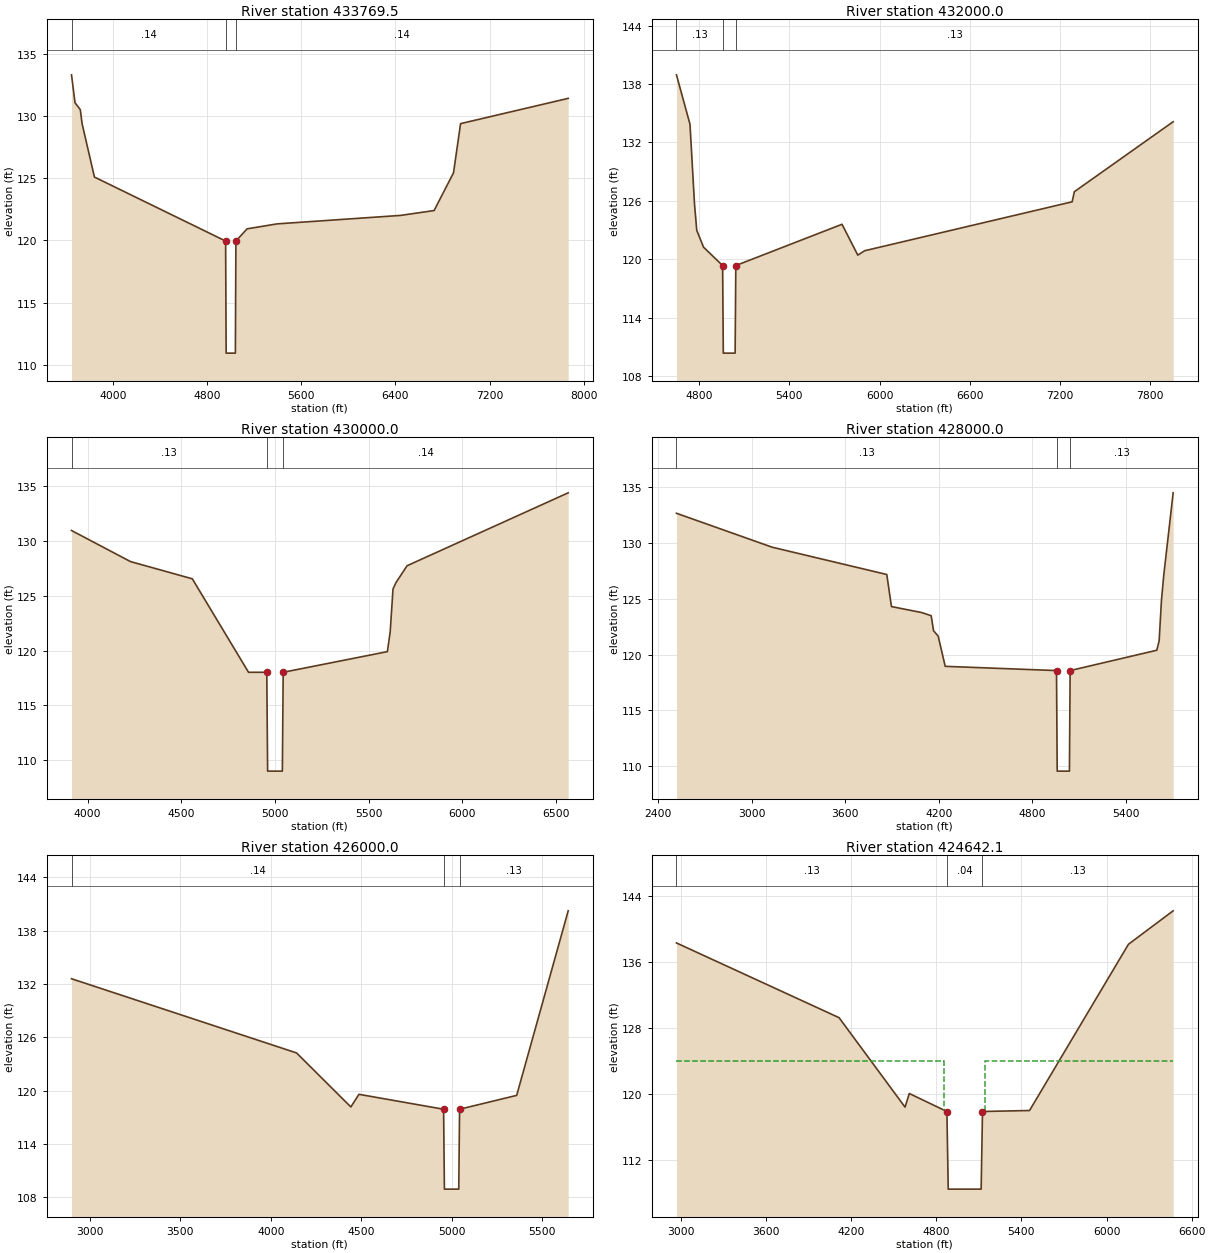
Type RM Length L Ch R = 1 ,433769.5,1769.518,1769.518,1769.518
BEGIN DESCRIPTION:
South River 217.0
END DESCRIPTION:
XS GIS Cut Line= 3
2111744.27764366528367.193779364 2110410.0841247528218.162269274
2107807.77775634529452.154772934
#Sta/Elev= 16
  3646.1   133.3  3676.1  131.06  3721.1   130.5  3736.1  129.38  3841.1  125.09
  4956.3  119.95  4960.8  110.95  5039.2  110.95  5043.7  119.95  5138.6  120.93
  5393.6  121.33  6443.6  122.01  6728.6   122.4  6893.6  125.43  6953.6  129.38
  7868.6  131.41
#Mann= 3 , 1 , 0
  3646.1     .14       0  4956.3     .04       0  5043.7     .14       0
Bank Sta=4956.3,5043.7
XS Rating Curve= 0 ,0
Exp/Cntr=0.3,0.1

Type RM Length L Ch R = 1 ,432000.0,2000.02,2000.02,2000.02
BEGIN DESCRIPTION:
South River 216.0
END DESCRIPTION:
XS GIS Cut Line= 3
2109415.85405047526729.3971840832109359.48347929527075.640692461
2107495.85459572529364.743887227
#Sta/Elev= 15
  4649.2  138.95  4739.2  133.87  4769.2  125.67  4784.2  122.97  4829.2  121.24
  4956.2  119.35  4960.7  110.35  5039.3  110.35  5043.8  119.35    5750  123.59
    5855  120.42    5900  120.87    7280   125.9    7295  126.94  7951.8  134.13
#Mann= 3 , 1 , 0
  4649.2     .13       0  4956.2     .04       0  5043.8     .13       0
Bank Sta=4956.2,5043.8
XS Rating Curve= 0 ,0
Exp/Cntr=0.3,0.1

Type RM Length L Ch R = 1 ,430000.0,2000.02,2000.02,2000.02
BEGIN DESCRIPTION:
South River 215.0
END DESCRIPTION:
XS GIS Cut Line= 3
2108222.02195375526651.1663913952107820.03788057527660.356617204
2107457.63420845 529183.20204772
#Sta/Elev= 14
  3913.7  130.93  4228.7   128.1  4558.7  126.53  4858.7  118.02  4956.2  118.02
  4960.7  109.02  5039.3  109.02  5043.8  118.02    5600   119.9    5615   121.7
    5630   125.6    5645  126.16    5705  127.72  6565.3  134.36
#Mann= 3 , 1 , 0
  3913.7     .13       0  4956.2     .04       0  5043.8     .14       0
Bank Sta=4956.2,5043.8
XS Rating Curve= 0 ,0
Exp/Cntr=0.3,0.1

Type RM Length L Ch R = 1 ,428000.0,2000.02,2000.02,2000.02
BEGIN DESCRIPTION:
South River 214.0
END DESCRIPTION:
XS GIS Cut Line= 3
2108422.67398689526498.2948423962106301.02248886  527788.3479141
2106264.91212297528492.425048293
#Sta/Elev= 18
  2516.9  132.65  3131.9  129.61  3866.9  127.17  3896.9   124.3  4091.9  123.76
  4151.9  123.48  4166.9  122.14  4196.9  121.65  4241.9  118.95  4956.2  118.57
  4960.7  109.57  5039.2  109.57  5043.7  118.57    5600  120.39    5615  121.23
    5630  124.88    5645  127.15    5705  134.48
#Mann= 3 , 1 , 0
  2516.9     .13       0  4956.2     .04       0  5043.7     .13       0
Bank Sta=4956.2,5043.7
XS Rating Curve= 0 ,0
Exp/Cntr=0.3,0.1

Type RM Length L Ch R = 1 ,426000.0,1357.914,1357.914,1357.914
BEGIN DESCRIPTION:
South River 213.0
END DESCRIPTION:
XS GIS Cut Line= 3
2108422.67398689526469.6245518892106321.22269354526411.773965707
2105731.63671945526150.191315172
#Sta/Elev= 10
  2897.8  132.59  4142.8  124.23  4442.8  118.15  4487.8  119.57  4955.8  117.89
  4960.3  108.89  5039.7  108.89  5044.2  117.89    5360  119.45    5645  140.24
#Mann= 3 , 1 , 0
  2897.8     .14       0  4955.8     .04       0  5044.2     .13       0
Bank Sta=4955.8,5044.2
XS Rating Curve= 0 ,0
Exp/Cntr=0.5,0.3

Type RM Length L Ch R = 1 ,424642.1,55.0006,55.0006,55.0006
BEGIN DESCRIPTION:
Upstream Section of Bridge/Culvert/Weir
END DESCRIPTION:
XS GIS Cut Line= 6
2109205.34191742526078.8805926032108288.41262646526028.200079073
2107896.75865796525917.618958589 2107330.0029152525507.524803233
2106744.82698579524982.2494807832106132.00077622524668.926305977
#Sta/Elev= 11
  2967.9  138.31  4114.4  129.26  4579.4  118.43  4609.4  120.08  4874.5   117.9
    4884   108.5    5116   108.5  5125.5   117.9  5457.2  118.02  6154.5  138.15
  6469.7   142.2
#Mann= 3 , 1 , 0
  2967.9     .13       0  4874.5     .04       0  5125.5     .13       0
#XS Ineff= 2 , 0
       0    4855     124    5145       0     124
Permanent Ineff=
       F       F
Bank Sta=4874.5,5125.5
XS Rating Curve= 0 ,0
Exp/Cntr=0.5,0.3

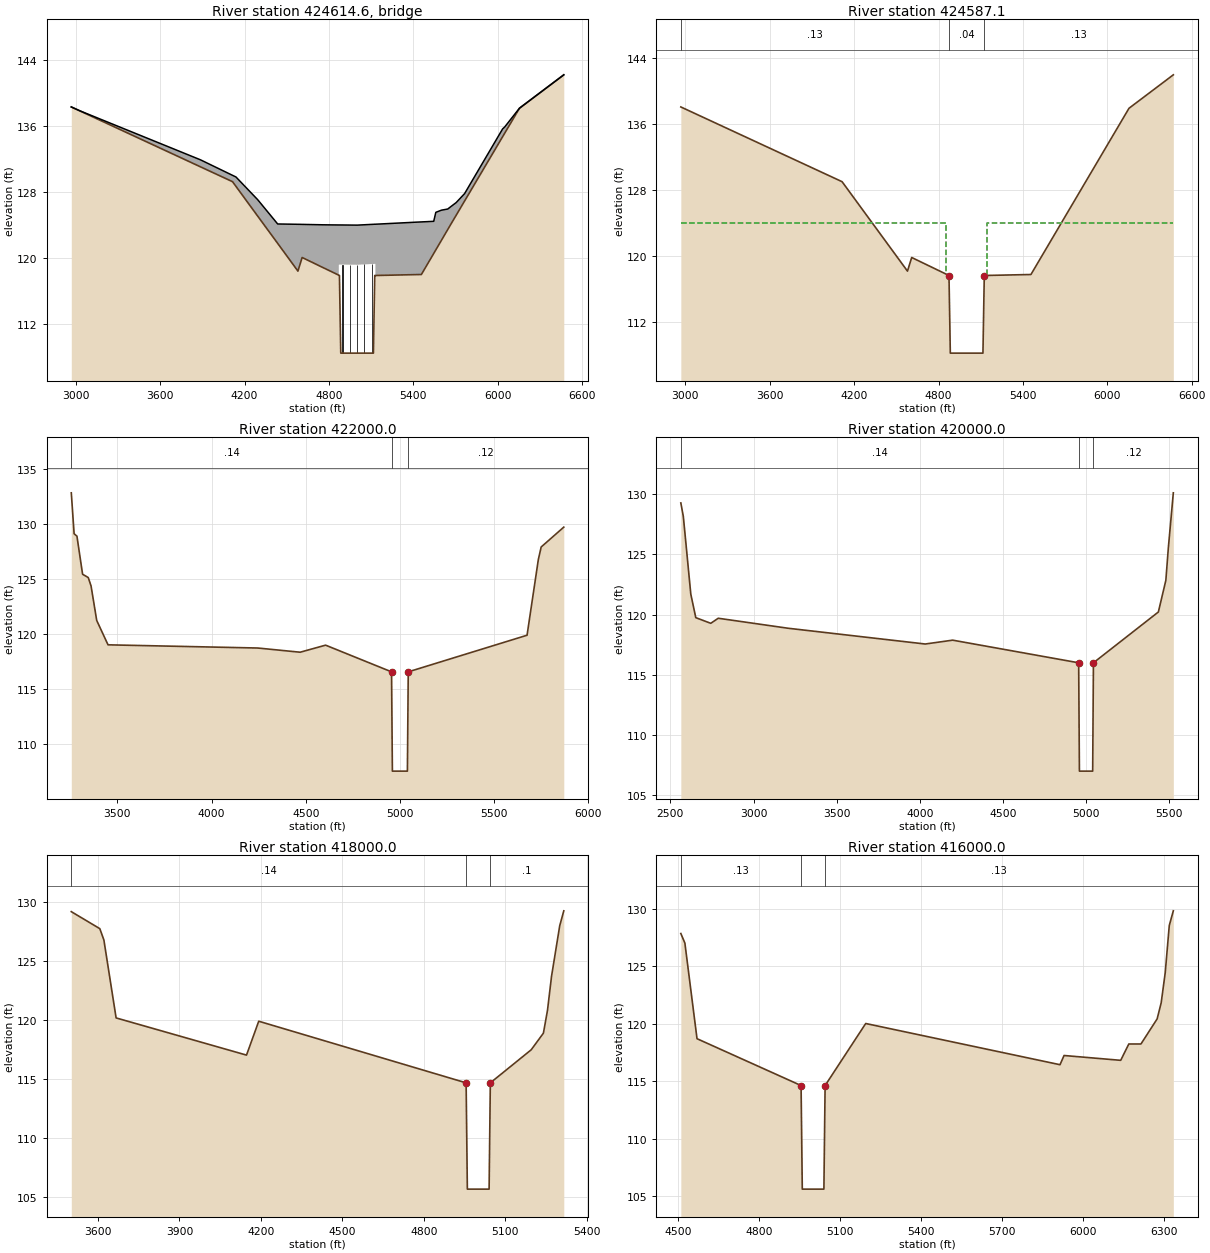
Type RM Length L Ch R = 3 ,424614.6,,,
BEGIN DESCRIPTION:
Green Path Rd-TOR
Structure ID: HLS-0497
Approximate Survey Structure
END DESCRIPTION:
Bridge Culvert--1,0,-1,-1, 0
Deck Dist Width WeirC Skew NumUp NumDn MinLoCord MaxHiCord MaxSubmerge Is_Ogee
10,35,2.6,0, 33, 33, , , 0.95, 0, 1,1,,
  2967.9  3027.9  3886.3  4114.4  4138.8  4293.3  4435.3  4579.4  4609.4  4757.3
 4869.91    4870  4870.1  4874.5    4884    5000    5116  5125.5  5129.8 5129.89
    5130  5457.2  5544.8  5559.8  5599.5  5644.5  5667.2  5704.5  5764.5  6034.7
  6049.7  6154.5  6469.7
  138.31  137.85  131.91  130.03  129.83  127.08  124.14   124.1  124.09  124.04
  124.02  124.02  124.02  124.02  124.02     124   124.1  124.11  124.11  124.11
  124.11  124.39  124.46  125.55  125.81  125.95  126.25  126.73  127.82  135.65
  135.89  138.16   142.2
  138.31  137.84  131.06  129.26  128.69  125.09  121.79  118.43  120.08  118.86
  117.94  119.22  119.22  119.22  119.22   119.2   119.3  119.31  119.31  119.31
   117.9  118.02  120.56     121  122.15  123.46  124.12  125.19  126.92   134.7
  135.13  138.15   142.2
  2967.9  3027.9  3886.3  4114.4  4138.8  4293.3  4435.3  4579.4  4609.4  4757.3
 4869.91    4870  4870.1  4874.5    4884    5000    5116  5125.5  5129.8 5129.89
    5130  5457.2  5544.8  5559.8  5599.5  5644.5  5667.2  5704.5  5764.5  6034.7
  6049.7  6154.5  6469.7
  138.31  137.85  131.91  130.03  129.83  127.08  124.14   124.1  124.09  124.04
  124.02  124.02  124.02  124.02  124.02     124   124.1  124.11  124.11  124.11
  124.11  124.39  124.46  125.55  125.81  125.95  126.25  126.73  127.82  135.65
  135.89  138.16   142.2
  138.06  137.59  130.81  129.01  128.44  124.84  121.54  118.18  119.83  118.61
  117.69  118.97  118.97  118.97  118.97  118.95  119.05  119.06  119.06  119.06
  117.65  117.77  120.31  120.75   121.9  123.21  123.87  124.94  126.67  134.45
  134.88   137.9  141.95
Pier Skew, UpSta & Num, DnSta & Num=  ,4896, 2 ,4896, 2 , 0 , 0 , 0 ,,
       1       1
   107.5  120.22
       1       1
  107.25  119.97
Pier Skew, UpSta & Num, DnSta & Num=  ,4948, 2 ,4948, 2 , 0 , 0 , 0 ,,
       1       1
   107.5  120.21
       1       1
  107.25  119.96
Pier Skew, UpSta & Num, DnSta & Num=  ,5000, 2 ,5000, 2 , 0 , 0 , 0 ,,
       1       1
   107.5   120.2
       1       1
  107.25  119.95
Pier Skew, UpSta & Num, DnSta & Num=  ,5052, 2 ,5052, 2 , 0 , 0 , 0 ,,
       1       1
   107.5  120.25
       1       1
  107.25     120
Pier Skew, UpSta & Num, DnSta & Num=  ,5104, 2 ,5104, 2 , 0 , 0 , 0 ,,
       1       1
   107.5  120.29
       1       1
  107.25  120.04
BR Coef= 1 , 1 , 0 ,1.25, 0 ,,,0.8,0,2,0,
WSPro=,,,, 1 ,,,, 0 ,,,, 0 ,,,,-1 ,-1 ,-1 , 0 , 0 , 0 , 0 , 0
BR U #Sta/Elev= 33
  2967.9  138.31  3027.9  137.84  3886.3  131.06  4114.4  129.26  4138.8  128.69
  4293.3  125.09  4435.3  121.79  4579.4  118.43  4609.4  120.08  4757.3  118.86
 4869.91  117.94    4870  117.94  4870.1  117.94  4874.5   117.9    4884   108.5
    5000   108.5    5116   108.5  5125.5   117.9  5129.8   117.9 5129.89   117.9
    5130   117.9  5457.2  118.02  5544.8  120.56  5559.8     121  5599.5  122.15
  5644.5  123.46  5667.2  124.12  5704.5  125.19  5764.5  126.92  6034.7   134.7
  6049.7  135.13  6154.5  138.15  6469.7   142.2
BR U #Mann= 3
  2967.9     .13  4874.5     .04  5125.5     .13
BR U Banks=4874.5,5125.5
BR D #Sta/Elev= 33
  2967.9  138.06  3027.9  137.59  3886.3  130.81  4114.4  129.01  4138.8  128.44
  4293.3  124.84  4435.3  121.54  4579.4  118.18  4609.4  119.83  4757.3  118.61
 4869.91  117.69    4870  117.69  4870.1  117.69  4874.5  117.65    4884  108.25
    5000  108.25    5116  108.25  5125.5  117.65  5129.8  117.65 5129.89  117.65
    5130  117.65  5457.2  117.77  5544.8  120.31  5559.8  120.75  5599.5   121.9
  5644.5  123.21  5667.2  123.87  5704.5  124.94  5764.5  126.67  6034.7  134.45
  6049.7  134.88  6154.5   137.9  6469.7  141.95
BR D #Mann= 3
  2967.9     .13  4874.5     .04  5125.5     .13
BR D Banks=4874.5,5125.5
BC Design=,, 0 ,, 0 ,,,,,,
BC HTab HWMax=142.2
BC Use User HTab Curves=0
BC User HTab FreeFlow(D)= 0

Type RM Length L Ch R = 1 ,424587.1,2587.126,2587.126,2587.126
BEGIN DESCRIPTION:
Downstream Section of Bridge/Culvert/Weir
END DESCRIPTION:
XS GIS Cut Line= 6
2109241.28228159526037.2401706732108324.35299064525986.559657143
2107932.69902213 525875.978536662107365.94327937525465.884381304
2106780.76734997524940.6090588532106167.94114039524627.285884048
#Sta/Elev= 11
  2967.9  138.05  4114.4     129  4579.4  118.17  4609.4  119.82  4874.5  117.64
    4884  108.24    5116  108.24  5125.5  117.64  5457.2  117.76  6154.5  137.89
  6469.7  141.94
#Mann= 3 , 1 , 0
  2967.9     .13       0  4874.5     .04       0  5125.5     .13       0
#XS Ineff= 2 , 0
       0    4855     124    5145       0     124
Permanent Ineff=
       F       F
Bank Sta=4874.5,5125.5
XS Rating Curve= 0 ,0
Exp/Cntr=0.5,0.3

Type RM Length L Ch R = 1 ,422000.0,2000.02,2000.02,2000.02
BEGIN DESCRIPTION:
South River 211.0
END DESCRIPTION:
XS GIS Cut Line= 3
2110049.46047061524059.6101319672108309.82284341523929.148810043
2107442.60405615523859.518104497
#Sta/Elev= 19
  3255.5   132.8  3270.5  129.09  3285.5  128.87  3315.5  125.42  3345.5  125.12
  3360.5  124.35  3390.5  121.23  3450.5  119.02  4245.5  118.73  4470.5  118.35
  4605.5  118.99  4955.6  116.57  4960.1  107.57  5039.8  107.57  5044.3  116.57
    5675  119.89    5735  126.76    5750  127.89    5870  129.69
#Mann= 3 , 1 , 0
  3255.5     .14       0  4955.6     .04       0  5044.3     .12       0
Bank Sta=4955.6,5044.3
XS Rating Curve= 0 ,0
Exp/Cntr=0.3,0.1

Type RM Length L Ch R = 1 ,420000.0,2000.02,2000.02,2000.02
BEGIN DESCRIPTION:
South River 210.0
END DESCRIPTION:
XS GIS Cut Line= 3
 2109571.9256319522256.9318659932107149.85108978522529.154624341
2106625.28577452522550.584841486
#Sta/Elev= 17
  2562.7  129.28  2577.7  128.16  2622.7   121.7  2652.7  119.75  2742.7  119.28
  2787.7   119.7  3207.7  118.87  4032.7  117.56  4197.7  117.88  4955.6     116
  4960.1     107  5039.9     107  5044.4     116    5435  120.22    5480  122.85
    5495  125.55    5525  130.12
#Mann= 3 , 1 , 0
  2562.7     .14       0  4955.6     .04       0  5044.4     .12       0
Bank Sta=4955.6,5044.4
XS Rating Curve= 0 ,0
Exp/Cntr=0.3,0.1

Type RM Length L Ch R = 1 ,418000.0,2000.02,2000.02,2000.02
BEGIN DESCRIPTION:
South River 209.0
END DESCRIPTION:
XS GIS Cut Line= 3
2109241.05227926521530.5745060412107909.74878958520843.997549171
2107612.95578227520738.466479858
#Sta/Elev= 16
  3502.1  129.16  3607.1  127.72  3622.1  126.76  3667.1  120.16  4147.1  117.01
  4192.1  119.88  4955.5  114.66    4960  105.66  5040.1  105.66  5044.6  114.66
    5195  117.46    5240  118.87    5255   120.8    5270   123.7    5300  127.96
    5315  129.23
#Mann= 3 , 1 , 0
  3502.1     .14       0  4955.5     .04       0  5044.6      .1       0
Bank Sta=4955.5,5044.6
XS Rating Curve= 0 ,0
Exp/Cntr=0.3,0.1

Type RM Length L Ch R = 1 ,416000.0,1824.619,1824.619,1824.619
BEGIN DESCRIPTION:
South River 208.0
END DESCRIPTION:
XS GIS Cut Line= 3
2109594.93586505520027.5292761542109287.32274811519645.855408772
2108090.97062585519053.399405601
#Sta/Elev= 18
  4509.8  127.85  4524.8  127.02  4569.8  118.71  4955.4  114.64  4959.9  105.64
    5040  105.64  5044.5  114.64    5195  120.03    5915  116.45    5930  117.25
    6140  116.83    6170  118.25    6215  118.25    6275  120.43    6290  121.83
    6305  124.45    6320  128.55    6335  129.82
#Mann= 3 , 1 , 0
  4509.8     .13       0  4955.4     .04       0  5044.5     .13       0
Bank Sta=4955.4,5044.5
XS Rating Curve= 0 ,0
Exp/Cntr=0.3,0.1

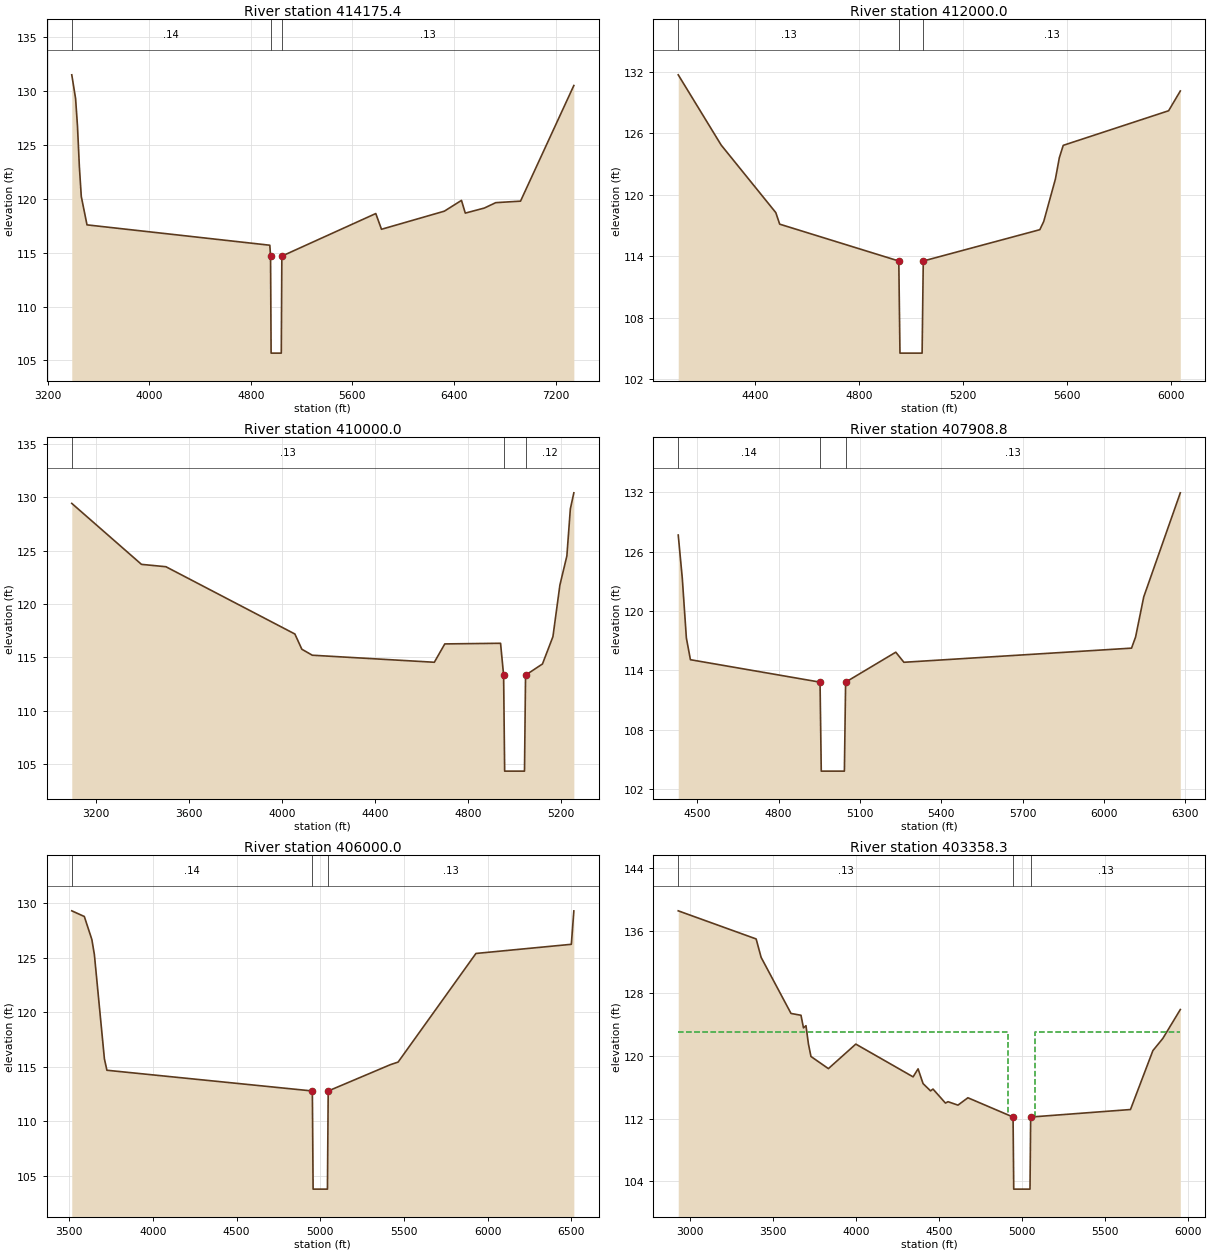
Type RM Length L Ch R = 1 ,414175.4,2175.422,2175.422,2175.422
BEGIN DESCRIPTION:
South River 207.0
END DESCRIPTION:
XS GIS Cut Line= 3
2110693.44699592520016.0091594242110534.29538329518424.453032684
2108196.30169313518707.285898541
#Sta/Elev= 20
  3389.8   131.5  3419.8  129.31  3434.8  126.74  3449.8  122.94  3464.8  120.21
  3509.8  117.58  4949.8  115.69  4955.4  114.68  4959.9  105.68    5040  105.68
  5044.5  114.68  5784.3  118.63  5829.3  117.17  6324.3  118.85  6459.3  119.85
  6489.3  118.67  6639.3  119.14  6729.3  119.64  6924.3  119.78  7344.3  130.51
#Mann= 3 , 1 , 0
  3389.8     .14       0  4955.4     .04       0  5044.5     .13       0
Bank Sta=4955.4,5044.5
XS Rating Curve= 0 ,0
Exp/Cntr=0.3,0.1

Type RM Length L Ch R = 1 ,412000.0,2000.02,2000.02,2000.02
BEGIN DESCRIPTION:
South River 206.0
END DESCRIPTION:
XS GIS Cut Line= 3
2109731.36724747  516730.8958724 2109036.5302069517294.871586989
2108010.97981532517434.473001527
#Sta/Elev= 15
  4105.1  131.73  4270.1  124.87  4480.1  118.27  4495.1  117.14  4952.9  113.54
  4957.4  104.54  5042.5  104.54    5047  113.54    5495   116.6    5510   117.4
    5555  121.56    5570  123.63    5585  124.84    5990  128.22    6035  130.15
#Mann= 3 , 1 , 0
  4105.1     .13       0  4952.9     .04       0    5047     .13       0
Bank Sta=4952.9,5047
XS Rating Curve= 0 ,0
Exp/Cntr=0.3,0.1

Type RM Length L Ch R = 1 ,410000.0,2091.221,2091.221,2091.221
BEGIN DESCRIPTION:
South River 205.0
END DESCRIPTION:
XS GIS Cut Line= 3
 2109852.0884707515986.9083338072107954.51924323515815.286594818
2107699.52665947515817.496617211
#Sta/Elev= 19
  3094.7  129.43  3394.7  123.71  3499.7  123.49  4054.7  117.18  4084.7  115.75
  4129.7  115.19  4654.7  114.53  4699.7  116.25  4939.7  116.31  4952.8  113.32
  4957.3  104.32  5042.7  104.32  5047.2  113.32    5120  114.37    5165  116.93
    5195  121.77    5225   124.5    5240  128.92    5255  130.42
#Mann= 3 , 1 , 0
  3094.7     .13       0  4952.8     .04       0  5047.2     .12       0
Bank Sta=4952.8,5047.2
XS Rating Curve= 0 ,0
Exp/Cntr=0.3,0.1

Type RM Length L Ch R = 1 ,407908.8,1908.819,1908.819,1908.819
BEGIN DESCRIPTION:
South River 204.0
END DESCRIPTION:
XS GIS Cut Line= 3
2110257.73258097514947.1177979352109683.91676667514879.617113972
2108415.66391586514748.185782219
#Sta/Elev= 14
  4429.5  127.67  4444.5  123.29  4459.5  117.26  4474.5  115.06  4952.8  112.79
  4957.3  103.79  5042.7  103.79  5047.2  112.79  5232.3  115.82  5262.3   114.8
  6102.3  116.23  6117.3  117.36  6147.3  121.41  6282.3  131.94
#Mann= 3 , 1 , 0
  4429.5     .14       0  4952.8     .04       0  5047.2     .13       0
Bank Sta=4952.8,5047.2
XS Rating Curve= 0 ,0
Exp/Cntr=0.3,0.1

Type RM Length L Ch R = 1 ,406000.0,2641.727,2641.727,2641.727
BEGIN DESCRIPTION:
South River 203.0
END DESCRIPTION:
XS GIS Cut Line= 3
2110852.52860785 513604.264191222109413.28402443513238.830488394
2107959.18929055 513664.13479787
#Sta/Elev= 15
  3515.1  129.29  3590.1  128.77  3635.1  126.66  3650.1  125.29  3710.1  115.72
  3725.1  114.67  4952.6  112.77  4957.1  103.77  5042.8  103.77  5047.3  112.77
    5420  115.19    5465  115.42    5930  125.38    6500  126.22    6515  129.28
#Mann= 3 , 1 , 0
  3515.1     .14       0  4952.6     .04       0  5047.3     .13       0
Bank Sta=4952.6,5047.3
XS Rating Curve= 0 ,0
Exp/Cntr=0.5,0.3

Type RM Length L Ch R = 1 ,403358.3,52.0005,52.0005,52.0005
BEGIN DESCRIPTION:
Upstream Section of Bridge/Culvert/Weir
END DESCRIPTION:
XS GIS Cut Line= 5
2110487.77491191511617.9940649662109671.58664173 511660.94450017
2108420.53396521511730.1852017642107723.92690671511770.635611635
2107469.40432771511786.325770619
#Sta/Elev= 28
    2931  138.52  3400.1  134.93  3430.1  132.58  3610.1  125.42  3670.1  125.19
  3685.1  123.58  3700.1  123.86  3715.1  121.51  3730.1  119.93  3835.1  118.38
  4000.1  121.51  4345.1  117.33  4375.1  118.35  4405.1  116.47  4450.1  115.54
  4465.1  115.77  4540.1  113.98  4555.1  114.16  4615.1  113.72  4675.1  114.66
    4947   112.2    4951     103    5049     103    5053   112.2    5654  113.16
    5789  120.68    5849  122.24    5954  125.92
#Mann= 3 , 1 , 0
    2931     .13       0    4947     .04       0    5053     .13       0
#XS Ineff= 2 , 0
       0    4918     123    5082       0     123
Permanent Ineff=
       F       F
Bank Sta=4947,5053
XS Rating Curve= 0 ,0
Exp/Cntr=0.5,0.3

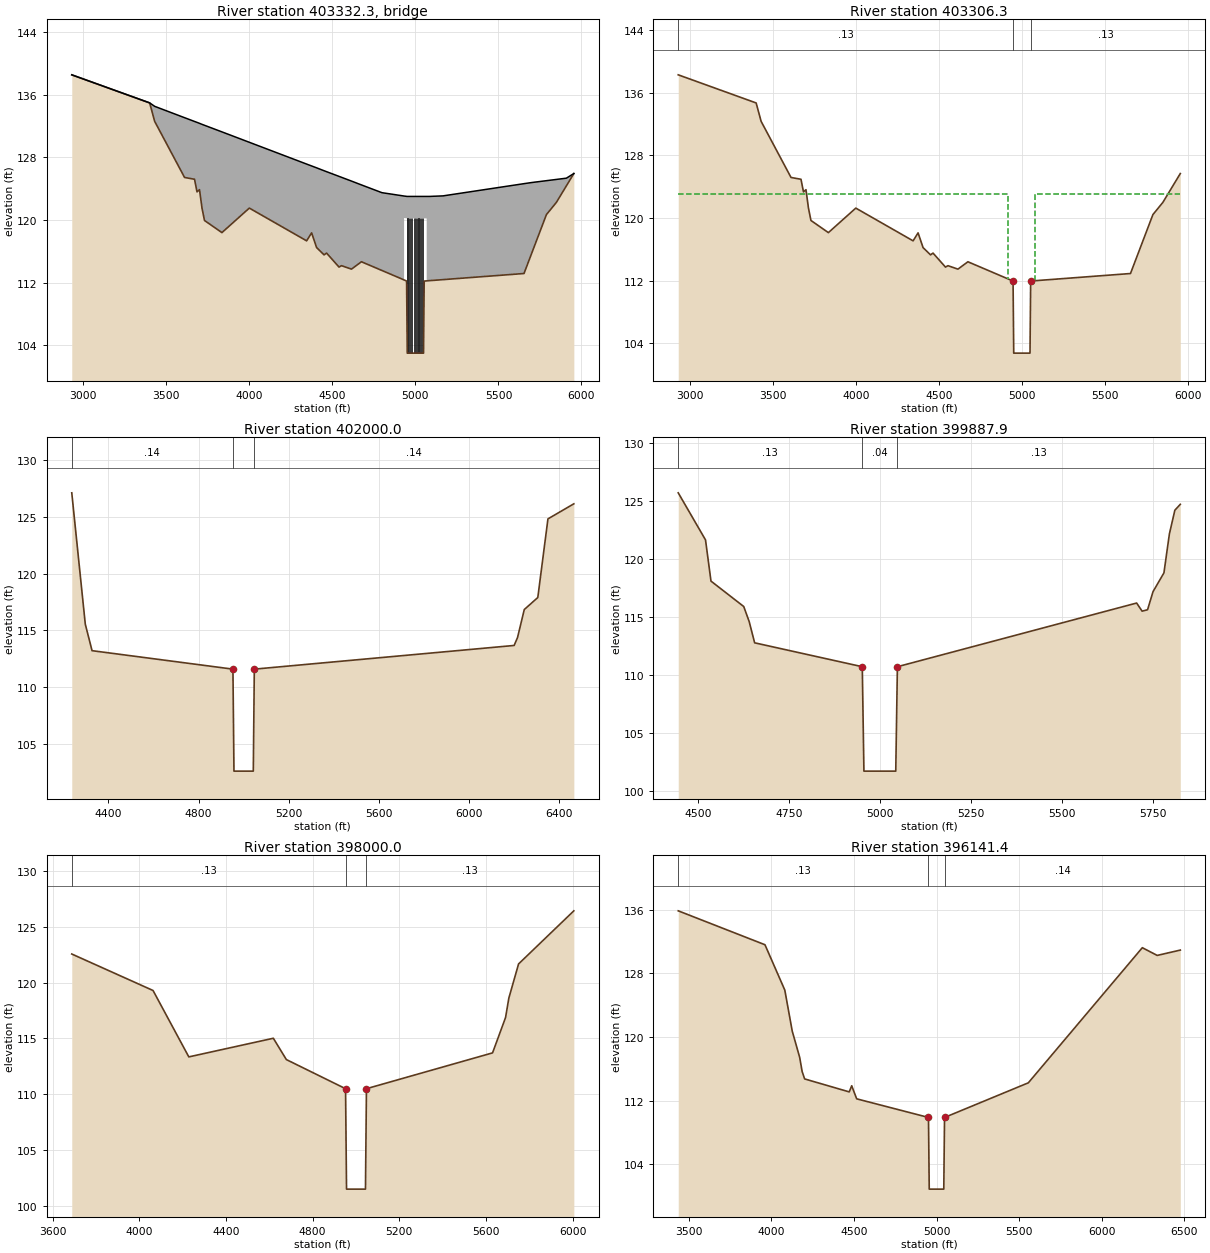
Type RM Length L Ch R = 3 ,403332.3,,,
BEGIN DESCRIPTION:
HWY 13-TOR
Structure ID: HLS-0495
Approximate Survey Structure
END DESCRIPTION:
Bridge Culvert--1,0,-1,-1, 0
Deck Dist Width WeirC Skew NumUp NumDn MinLoCord MaxHiCord MaxSubmerge Is_Ogee
10,32,2.6,0, 41, 41, , , 0.95, 0, 1,1,,
    2931  3400.1  3430.1  3610.1  3670.1  3685.1  3700.1  3715.1  3730.1  3835.1
  4000.1  4345.1  4375.1  4405.1  4450.1  4465.1  4540.1  4555.1  4615.1  4675.1
  4798.3 4931.91    4932    4947  4948.7    4949    4951    5000    5049    5051
    5053 5067.89    5068  5085.1  5166.3    5654    5699    5789    5849    5909
    5954
  138.52  134.94   134.5  133.05  132.57  132.45  132.33   132.2  132.08  131.24
  129.91  127.13  126.89  126.65  126.28  126.16  125.56  125.44  124.96  124.47
  123.48  123.05  123.05  123.01     123     123     123     123     123     123
     123     123     123     123  123.07  124.63  124.77  125.01  125.17  125.33
  125.92
  138.52  134.93  132.58  125.42  125.19  123.58  123.86  121.51  119.93  118.38
  121.51  117.33  118.35  116.47  115.54  115.77  113.98  114.16  113.72  114.66
  113.55  112.34  120.25  120.21   120.2   120.2   120.2   120.2   120.2   120.2
   120.2   120.2  112.22  112.25  112.38  113.16  115.67  120.68  122.24  124.34
  125.92
    2931  3400.1  3430.1  3610.1  3670.1  3685.1  3700.1  3715.1  3730.1  3835.1
  4000.1  4345.1  4375.1  4405.1  4450.1  4465.1  4540.1  4555.1  4615.1  4675.1
  4798.3 4931.91    4932    4947  4948.7    4949    4951    5000    5049    5051
    5053 5067.89    5068  5085.1  5166.3    5654    5699    5789    5849    5909
    5954
  138.52  134.94   134.5  133.05  132.57  132.45  132.33   132.2  132.08  131.24
  129.91  127.13  126.89  126.65  126.28  126.16  125.56  125.44  124.96  124.47
  123.48  123.05  123.05  123.01     123     123     123     123     123     123
     123     123     123     123  123.07  124.63  124.77  125.01  125.17  125.33
  125.92
  138.27  134.68  132.33  125.17  124.94  123.33  123.61  121.26  119.68  118.13
  121.26  117.08   118.1  116.22  115.29  115.52  113.73  113.91  113.47  114.41
   113.3  112.09     120  119.96  119.95  119.95  119.95  119.95  119.95  119.95
  119.95  119.95  111.97     112  112.13  112.91  115.42  120.43  121.99  124.09
  125.67
Pier Skew, UpSta & Num, DnSta & Num=  ,4952.7, 2 ,4952.7, 2 , 0 , 0 , 0 ,,
       1       1
     102   121.2
       1       1
  101.75  120.95
Pier Skew, UpSta & Num, DnSta & Num=  ,4960, 2 ,4960, 2 , 0 , 0 , 0 ,,
       1       1
     102   121.2
       1       1
  101.75  120.95
Pier Skew, UpSta & Num, DnSta & Num=  ,4967.3, 2 ,4967.3, 2 , 0 , 0 , 0 ,,
       1       1
     102   121.2
       1       1
  101.75  120.95
Pier Skew, UpSta & Num, DnSta & Num=  ,4974.5, 2 ,4974.5, 2 , 0 , 0 , 0 ,,
       1       1
     102   121.2
       1       1
  101.75  120.95
Pier Skew, UpSta & Num, DnSta & Num=  ,4981.8, 2 ,4981.8, 2 , 0 , 0 , 0 ,,
       1       1
     102   121.2
       1       1
  101.75  120.95
Pier Skew, UpSta & Num, DnSta & Num=  ,4989.1, 2 ,4989.1, 2 , 0 , 0 , 0 ,,
       1       1
     102   121.2
       1       1
  101.75  120.95
Pier Skew, UpSta & Num, DnSta & Num=  ,4996.4, 2 ,4996.4, 2 , 0 , 0 , 0 ,,
       1       1
     102   121.2
       1       1
  101.75  120.95
Pier Skew, UpSta & Num, DnSta & Num=  ,5003.7, 2 ,5003.7, 2 , 0 , 0 , 0 ,,
       1       1
     102   121.2
       1       1
  101.75  120.95
Pier Skew, UpSta & Num, DnSta & Num=  ,5011, 2 ,5011, 2 , 0 , 0 , 0 ,,
       1       1
     102   121.2
       1       1
  101.75  120.95
Pier Skew, UpSta & Num, DnSta & Num=  ,5018.3, 2 ,5018.3, 2 , 0 , 0 , 0 ,,
       1       1
     102   121.2
       1       1
  101.75  120.95
Pier Skew, UpSta & Num, DnSta & Num=  ,5025.5, 2 ,5025.5, 2 , 0 , 0 , 0 ,,
       1       1
     102   121.2
       1       1
  101.75  120.95
Pier Skew, UpSta & Num, DnSta & Num=  ,5032.8, 2 ,5032.8, 2 , 0 , 0 , 0 ,,
       1       1
     102   121.2
       1       1
  101.75  120.95
Pier Skew, UpSta & Num, DnSta & Num=  ,5040.1, 2 ,5040.1, 2 , 0 , 0 , 0 ,,
       1       1
     102   121.2
       1       1
  101.75  120.95
Pier Skew, UpSta & Num, DnSta & Num=  ,5047.4, 2 ,5047.4, 2 , 0 , 0 , 0 ,,
       1       1
     102   121.2
       1       1
  101.75  120.95
Abutment Skew #Up #Dn= , 2 , 2
  4931.8    4949
  120.25   107.6
  4931.8    4949
     120  107.35
Abutment Skew #Up #Dn= , 2 , 2
    5051 5068.09
   107.6   120.2
    5051 5068.09
  107.35  119.95
BR Coef= 1 , 1 , 0 ,1.25, 0 ,,,0.8,0,2,0,
WSPro=,,,, 1 ,,,, 0 ,,,, 0 ,,,,-1 ,-1 ,-1 , 0 , 0 , 0 , 0 , 0
BR U #Sta/Elev= 41
    2931  138.52  3400.1  134.93  3430.1  132.58  3610.1  125.42  3670.1  125.19
  3685.1  123.58  3700.1  123.86  3715.1  121.51  3730.1  119.93  3835.1  118.38
  4000.1  121.51  4345.1  117.33  4375.1  118.35  4405.1  116.47  4450.1  115.54
  4465.1  115.77  4540.1  113.98  4555.1  114.16  4615.1  113.72  4675.1  114.66
  4798.3  113.55 4931.91  112.34    4932  112.34    4947   112.2  4948.7  108.29
    4949   107.6    4951     103    5000     103    5049     103    5051   107.6
    5053   112.2 5067.89  112.22    5068  112.22  5085.1  112.25  5166.3  112.38
    5654  113.16    5699  115.67    5789  120.68    5849  122.24    5909  124.34
    5954  125.92
BR U #Mann= 3
    2931     .13    4947     .04    5053     .13
BR U Banks=4947,5053
BR D #Sta/Elev= 41
    2931  138.27  3400.1  134.68  3430.1  132.33  3610.1  125.17  3670.1  124.94
  3685.1  123.33  3700.1  123.61  3715.1  121.26  3730.1  119.68  3835.1  118.13
  4000.1  121.26  4345.1  117.08  4375.1   118.1  4405.1  116.22  4450.1  115.29
  4465.1  115.52  4540.1  113.73  4555.1  113.91  4615.1  113.47  4675.1  114.41
  4798.3   113.3 4931.91  112.09    4932  112.09    4947  111.95  4948.7  108.04
    4949  107.35    4951  102.75    5000  102.75    5049  102.75    5051  107.35
    5053  111.95 5067.89  111.97    5068  111.97  5085.1     112  5166.3  112.13
    5654  112.91    5699  115.42    5789  120.43    5849  121.99    5909  124.09
    5954  125.67
BR D #Mann= 3
    2931     .13    4947     .04    5053     .13
BR D Banks=4947,5053
BC Design=,, 0 ,, 0 ,,,,,,
BC HTab HWMax=138.52
BC Use User HTab Curves=0
BC User HTab FreeFlow(D)= 0

Type RM Length L Ch R = 1 ,403306.3,1306.313,1306.313,1306.313
BEGIN DESCRIPTION:
Downstream Section of Bridge/Culvert/Weir
END DESCRIPTION:
XS GIS Cut Line= 5
2110485.81489205511566.0335384672109669.62662187 511608.98397367
2108418.57394535511678.2246752642107721.96688685511718.675085136
2107467.44430785511734.365244119
#Sta/Elev= 28
    2931  138.27  3400.1  134.68  3430.1  132.33  3610.1  125.17  3670.1  124.94
  3685.1  123.33  3700.1  123.61  3715.1  121.26  3730.1  119.68  3835.1  118.13
  4000.1  121.26  4345.1  117.08  4375.1   118.1  4405.1  116.22  4450.1  115.29
  4465.1  115.52  4540.1  113.73  4555.1  113.91  4615.1  113.47  4675.1  114.41
    4947  111.95    4951  102.75    5049  102.75    5053  111.95    5654  112.91
    5789  120.43    5849  121.99    5954  125.67
#Mann= 3 , 1 , 0
    2931     .13       0    4947     .04       0    5053     .13       0
#XS Ineff= 2 , 0
       0    4918     123    5082       0     123
Permanent Ineff=
       F       F
Bank Sta=4947,5053
XS Rating Curve= 0 ,0
Exp/Cntr=0.5,0.3

Type RM Length L Ch R = 1 ,402000.0,2112.121,2112.121,2112.121
BEGIN DESCRIPTION:
South River 201.0
END DESCRIPTION:
XS GIS Cut Line= 3
2109130.18115584510395.001672767 2108367.7934308510388.851610451
 2107409.8637244511497.202841027
#Sta/Elev= 13
  4237.6  127.14  4297.6  115.55  4327.6  113.21  4952.6  111.58  4957.1  102.58
  5042.9  102.58  5047.4  111.58    6200  113.67    6215  114.36    6245  116.84
    6305   117.9    6350  124.84  6464.9  126.17
#Mann= 3 , 1 , 0
  4237.6     .14       0  4952.6     .04       0  5047.4     .14       0
Bank Sta=4952.6,5047.4
XS Rating Curve= 0 ,0
Exp/Cntr=0.3,0.1

Type RM Length L Ch R = 1 ,399887.9,1887.919,1887.919,1887.919
BEGIN DESCRIPTION:
South River 200.0
END DESCRIPTION:
XS GIS Cut Line= 3
2108797.50778497 508915.296679382108279.35253466508716.744667515
2107483.49447048508499.702468294
#Sta/Elev= 18
  4445.9  125.69  4520.9  121.63  4535.9  118.08  4625.9  115.89  4640.9  114.59
  4655.9  112.76  4951.7   110.7  4956.2   101.7  5043.7   101.7  5048.2   110.7
  5705.7  116.19  5720.7  115.49  5735.7  115.61  5750.7  117.17  5780.7  118.79
  5795.7  122.15  5810.7  124.19  5825.7   124.7
#Mann= 3 , 1 , 0
  4445.9     .13       0  4951.7     .04       0  5048.2     .13       0
Bank Sta=4951.7,5048.2
XS Rating Curve= 0 ,0
Exp/Cntr=0.3,0.1

Type RM Length L Ch R = 1 ,398000.0,1858.619,1858.619,1858.619
BEGIN DESCRIPTION:
South River 199.0
END DESCRIPTION:
XS GIS Cut Line= 3
2109559.70550808508019.2475999952108686.09665607507041.267690431
2107729.51696335506733.064567505
#Sta/Elev= 14
  3688.7  122.57  4063.7   119.3  4228.7  113.35  4618.7  115.02  4678.7  113.11
  4951.8   110.5  4956.3   101.5  5043.7   101.5  5048.2   110.5    5630  113.71
    5690  116.88    5705  118.61    5750  121.68    6005  126.44
#Mann= 3 , 1 , 0
  3688.7     .13       0  4951.8     .04       0  5048.2     .13       0
Bank Sta=4951.8,5048.2
XS Rating Curve= 0 ,0
Exp/Cntr=0.3,0.1

Type RM Length L Ch R = 1 ,396141.4,2141.422,2141.422,2141.422
BEGIN DESCRIPTION:
South River 198.0
END DESCRIPTION:
XS GIS Cut Line= 3
2110696.72702916505984.0669781472109253.94240987 505420.33126599
2107772.94740342505257.899620121
#Sta/Elev= 18
  3436.8  135.85  3961.8  131.59  4081.8   125.9  4126.8  120.75  4171.8  117.45
  4186.8  115.67  4201.8  114.74  4471.8  113.11  4486.8  113.88  4516.8  112.24
  4951.5   109.9    4956   100.9  5044.1   100.9  5048.6   109.9  5555.8  114.25
  6245.8  131.22  6335.8  130.25  6475.7  130.92
#Mann= 3 , 1 , 0
  3436.8     .13       0  4951.5     .04       0  5048.6     .14       0
Bank Sta=4951.5,5048.6
XS Rating Curve= 0 ,0
Exp/Cntr=0.3,0.1