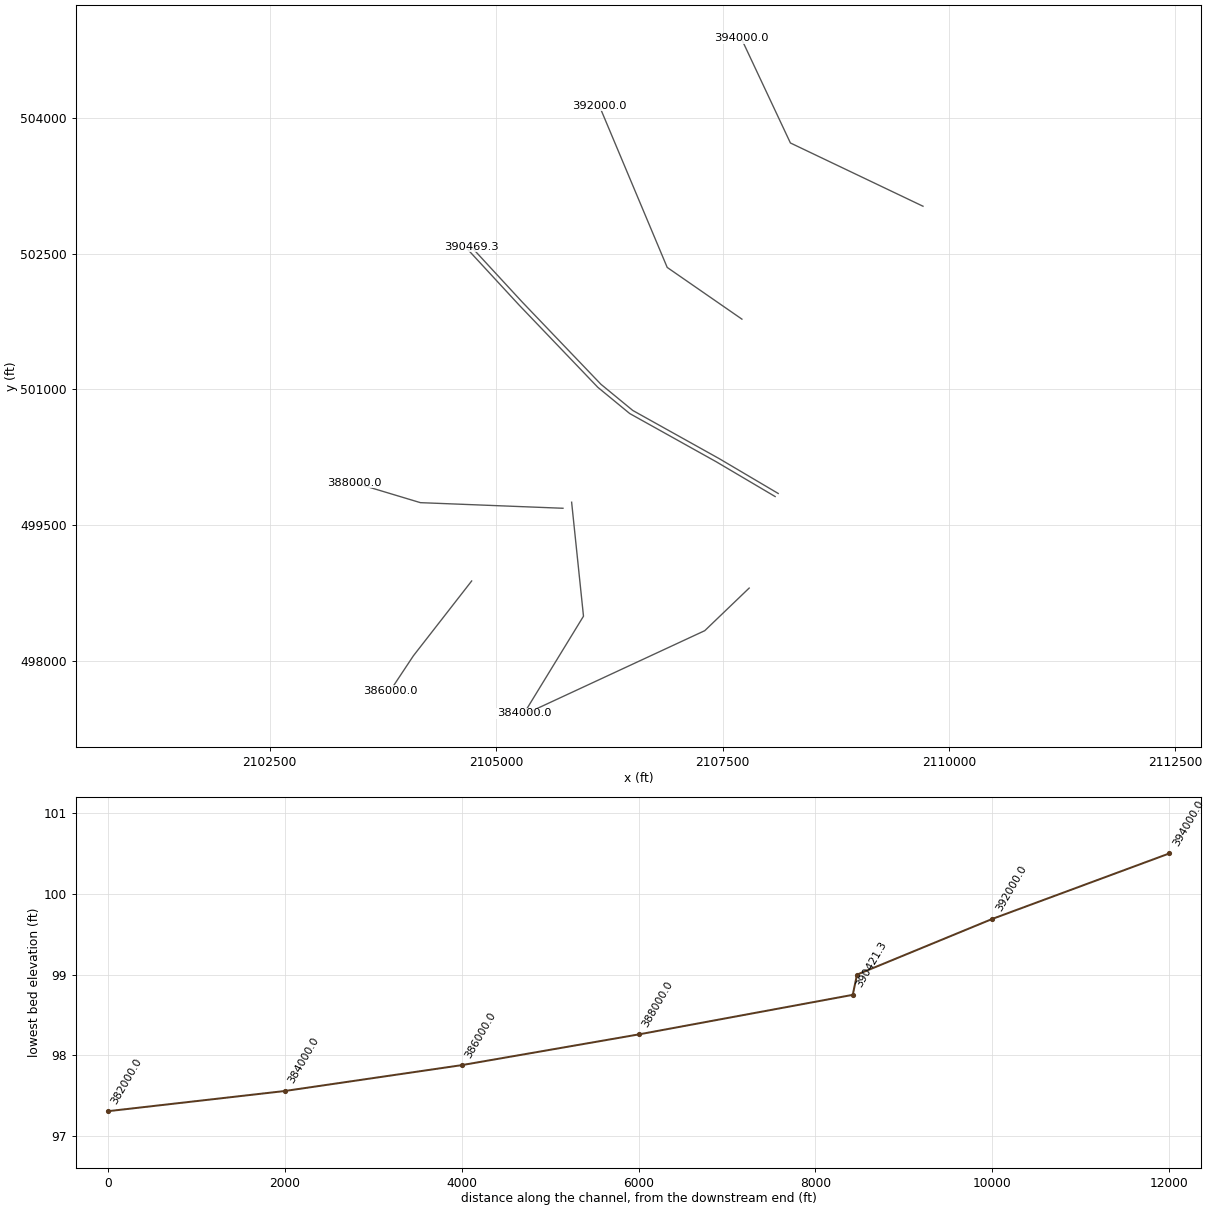
HEC-RAS study B4950SOUTHRIVERS.prj: B4950 SOUTH RIVER SR1851

--- B4950SOUTHRIVERS.g03 (geometry) --- (continued)

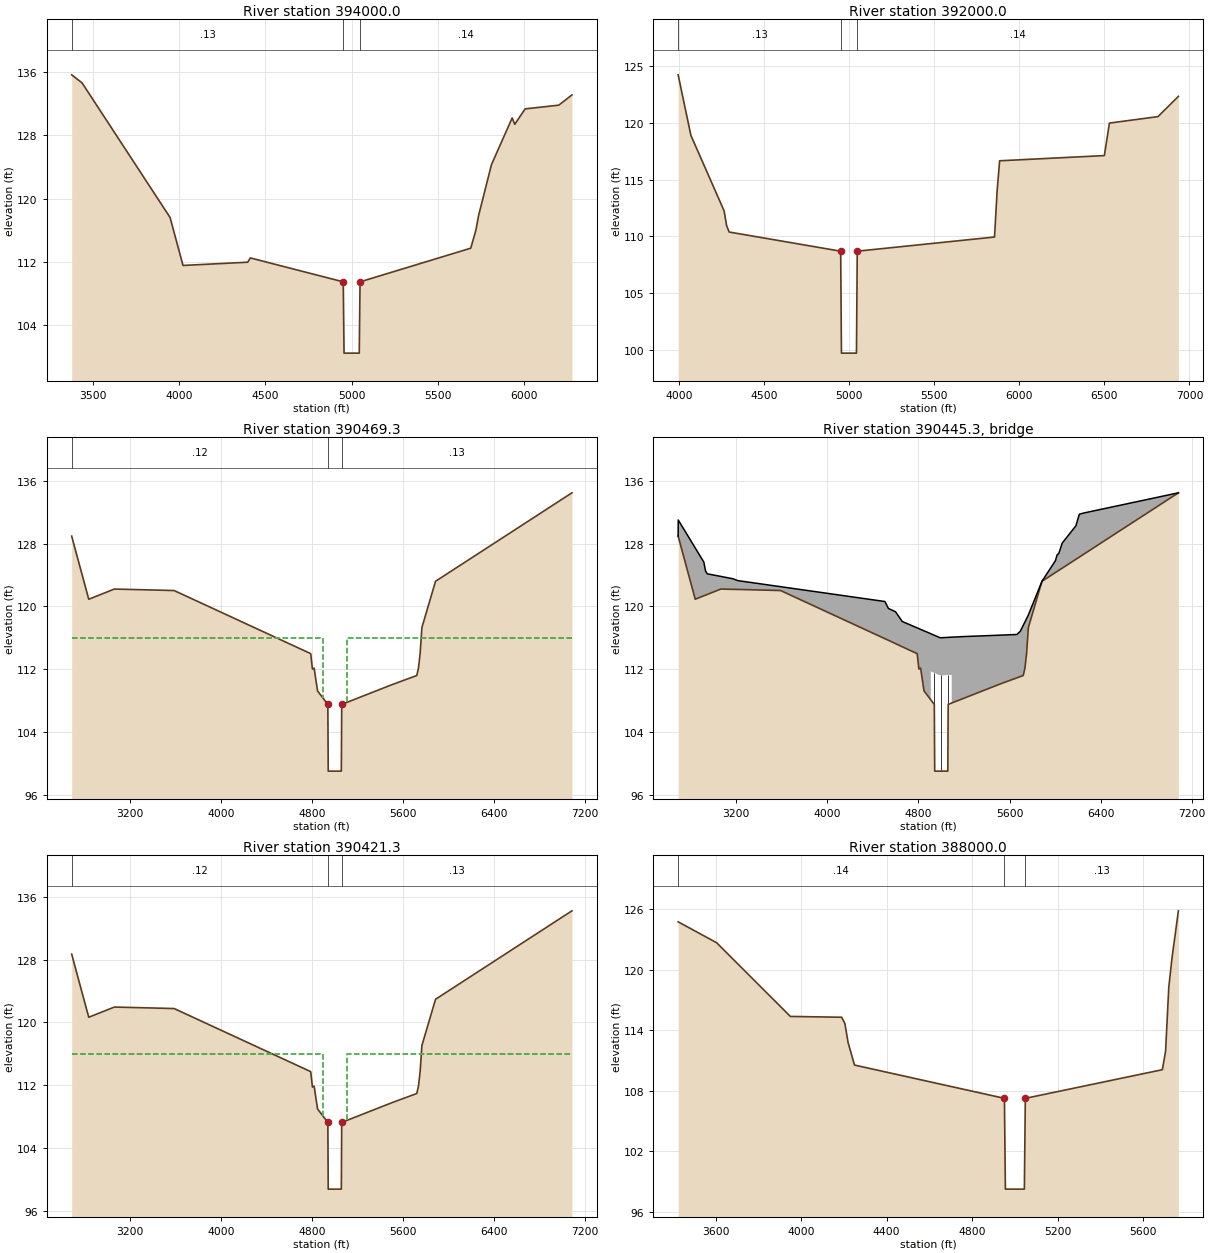
Type RM Length L Ch R = 1 ,394000.0,2000.02,2000.02,2000.02
BEGIN DESCRIPTION:
South River 197.0
END DESCRIPTION:
XS GIS Cut Line= 3
2109712.57705708503022.0669651282108248.70222409 503720.56404278
2107706.06672573 504875.70574747
#Sta/Elev= 19
    3378  135.64    3438  134.63    3948  117.63    4023  111.57    4398  111.98
    4413  112.52  4951.4   109.5  4955.9   100.5  5044.1   100.5  5048.6   109.5
    5690  113.75    5720  116.04    5735  117.83    5810   124.3    5930   130.2
    5945  129.39    6005  131.34    6200  131.81  6276.2   133.1
#Mann= 3 , 1 , 0
    3378     .13       0  4951.4     .04       0  5048.6     .14       0
Bank Sta=4951.4,5048.6
XS Rating Curve= 0 ,0
Exp/Cntr=0.3,0.1

Type RM Length L Ch R = 1 ,392000.0,1530.715,1530.715,1530.715
BEGIN DESCRIPTION:
South River 196.0
END DESCRIPTION:
XS GIS Cut Line= 3
2107713.58680193501775.3743327822106888.52844188502346.430119112
2106139.23084948504130.488196414
#Sta/Elev= 16
  3996.6  124.26  4071.6  118.91  4266.6  112.25  4281.6  110.93  4296.6  110.38
  4951.3  108.69  4955.8   99.69  5044.1   99.69  5048.6  108.69    5855  109.94
    5870  113.97    5885  116.67    6500  117.13    6530     120    6815  120.57
    6935  122.36
#Mann= 3 , 1 , 0
  3996.6     .13       0  4951.3     .04       0  5048.6     .14       0
Bank Sta=4951.3,5048.6
XS Rating Curve= 0 ,0
Exp/Cntr=0.5,0.3

Type RM Length L Ch R = 1 ,390469.3,48.0005,48.0005,48.0005
BEGIN DESCRIPTION:
Upstream Section of Bridge/Culvert/Weir
END DESCRIPTION:
XS GIS Cut Line= 6
2108114.09086012499850.844832127 2107464.0842738500234.578720382
2106508.65459273500767.1241164982106156.24102184501056.887052575
 2105286.9522136501965.3262575052104723.09650023502576.172447019
#Sta/Elev= 19
  2688.6  128.94  2838.6   120.9  3063.6   122.2  3588.6  122.01  4788.6  113.97
  4803.6  112.01  4818.6  112.12  4848.6  109.22    4939   107.5  4942.5      99
  5057.5      99    5061   107.5  5510.2  110.06  5720.2  111.18  5735.2  112.12
  5750.2  114.04  5765.2  117.29  5885.2  123.19  7083.4  134.46
#Mann= 3 , 1 , 0
  2688.6     .12       0    4939    .045       0    5061     .13       0
#XS Ineff= 2 , 0
       0    4895     116    5105       0     116
Permanent Ineff=
       F       F
Bank Sta=4939,5061
XS Rating Curve= 0 ,0
Exp/Cntr=0.5,0.3

Type RM Length L Ch R = 3 ,390445.3,,,
BEGIN DESCRIPTION:
Hayes Mill Rd-TOR
Structure ID: HLS-0494
Approximate Survey Structure
END DESCRIPTION:
Bridge Culvert--1,0,-1,-1, 0
Deck Dist Width WeirC Skew NumUp NumDn MinLoCord MaxHiCord MaxSubmerge Is_Ogee
10,28,2.6,0, 48, 48, , , 0.95, 0, 1,1,,
  2688.6  2689.4  2838.6  2914.4  2929.4  2944.4  3063.6  3169.4  3214.4  3588.6
  4505.6  4535.6  4598.1  4658.1  4788.6  4803.6  4818.6  4848.6 4907.91    4908
  4908.1    4939  4942.5  4989.3    5000  5005.8  5057.5    5061  5091.8 5091.89
    5092  5189.3  5510.2  5663.5  5693.5  5720.2  5735.2  5750.2  5765.2  5885.2
  6002.9  6017.9  6032.9  6062.9  6182.9  6212.9  6252.1  7083.4
  128.94     131  127.44  125.63   124.5  124.14  123.81  123.51  123.27   122.5
  120.61  119.73  119.31  118.06  117.25  117.16  117.06  116.88  116.51  116.51
  116.51  116.31  116.29     116     116     116  116.04  116.04  116.07  116.07
  116.07  116.14  116.32  116.41   116.8  117.58  118.01  118.45  118.89   123.2
  125.81  126.55  126.74  128.06  130.26  131.73  131.89  134.46
  128.94   128.9   120.9  121.34  121.42  121.51   122.2  122.16  122.15  122.01
  115.87  115.67  115.25  114.84  113.97  112.01  112.12  109.22  108.09  111.71
  111.71  111.51  111.49   111.2   111.2   111.2  111.24  111.24  111.27  111.27
  107.68  108.23  110.06  110.88  111.04  111.18  112.12  114.04  117.29  123.19
   124.3  124.44  124.58  124.86  125.99  126.27  126.64  134.46
  2688.6  2689.4  2838.6  2914.4  2929.4  2944.4  3063.6  3169.4  3214.4  3588.6
  4505.6  4535.6  4598.1  4658.1  4788.6  4803.6  4818.6  4848.6 4907.91    4908
  4908.1    4939  4942.5  4989.3    5000  5005.8  5057.5    5061  5091.8 5091.89
    5092  5189.3  5510.2  5663.5  5693.5  5720.2  5735.2  5750.2  5765.2  5885.2
  6002.9  6017.9  6032.9  6062.9  6182.9  6212.9  6252.1  7083.4
  128.94     131  127.44  125.63   124.5  124.14  123.81  123.51  123.27   122.5
  120.61  119.73  119.31  118.06  117.25  117.16  117.06  116.88  116.51  116.51
  116.51  116.31  116.29     116     116     116  116.04  116.04  116.07  116.07
  116.07  116.14  116.32  116.41   116.8  117.58  118.01  118.45  118.89   123.2
  125.81  126.55  126.74  128.06  130.26  131.73  131.89  134.46
  128.69  128.65  120.65  121.09  121.17  121.26  121.95  121.91   121.9  121.76
  115.62  115.42     115  114.59  113.72  111.76  111.87  108.97  107.84  111.46
  111.46  111.26  111.24  110.95  110.95  110.95  110.99  110.99  111.02  111.02
  107.43  107.98  109.81  110.63  110.79  110.93  111.87  113.79  117.04  122.94
  124.05  124.19  124.33  124.61  125.74  126.02  126.39  134.21
Pier Skew, UpSta & Num, DnSta & Num=  ,4938.7, 2 ,4938.7, 2 , 0 , 0 , 0 ,,
     1.5     1.5
  105.41  112.52
     1.5     1.5
  105.16  112.27
Pier Skew, UpSta & Num, DnSta & Num=  ,5000, 2 ,5000, 2 , 0 , 0 , 0 ,,
     1.5     1.5
      98   112.2
     1.5     1.5
   97.75  111.95
Pier Skew, UpSta & Num, DnSta & Num=  ,5061.3, 2 ,5061.3, 2 , 0 , 0 , 0 ,,
     1.5     1.5
  105.41  112.24
     1.5     1.5
  105.16  111.99
BR Coef= 1 , 1 , 0 ,1.25, 0 ,,,0.8,0,2,0,
WSPro=,,,, 1 ,,,, 0 ,,,, 0 ,,,,-1 ,-1 ,-1 , 0 , 0 , 0 , 0 , 0
BR U #Sta/Elev= 48
  2688.6  128.94  2689.4   128.9  2838.6   120.9  2914.4  121.34  2929.4  121.42
  2944.4  121.51  3063.6   122.2  3169.4  122.16  3214.4  122.15  3588.6  122.01
  4505.6  115.87  4535.6  115.67  4598.1  115.25  4658.1  114.84  4788.6  113.97
  4803.6  112.01  4818.6  112.12  4848.6  109.22 4907.91  108.09    4908  108.09
  4908.1  108.09    4939   107.5  4942.5      99  4989.3      99    5000      99
  5005.8      99  5057.5      99    5061   107.5  5091.8  107.68 5091.89  107.68
    5092  107.68  5189.3  108.23  5510.2  110.06  5663.5  110.88  5693.5  111.04
  5720.2  111.18  5735.2  112.12  5750.2  114.04  5765.2  117.29  5885.2  123.19
  6002.9   124.3  6017.9  124.44  6032.9  124.58  6062.9  124.86  6182.9  125.99
  6212.9  126.27  6252.1  126.64  7083.4  134.46
BR U #Mann= 3
  2688.6     .12    4939    .045    5061     .13
BR U Banks=4939,5061
BR D #Sta/Elev= 48
  2688.6  128.69  2689.4  128.65  2838.6  120.65  2914.4  121.09  2929.4  121.17
  2944.4  121.26  3063.6  121.95  3169.4  121.91  3214.4   121.9  3588.6  121.76
  4505.6  115.62  4535.6  115.42  4598.1     115  4658.1  114.59  4788.6  113.72
  4803.6  111.76  4818.6  111.87  4848.6  108.97 4907.91  107.84    4908  107.84
  4908.1  107.84    4939  107.25  4942.5   98.75  4989.3   98.75    5000   98.75
  5005.8   98.75  5057.5   98.75    5061  107.25  5091.8  107.43 5091.89  107.43
    5092  107.43  5189.3  107.98  5510.2  109.81  5663.5  110.63  5693.5  110.79
  5720.2  110.93  5735.2  111.87  5750.2  113.79  5765.2  117.04  5885.2  122.94
  6002.9  124.05  6017.9  124.19  6032.9  124.33  6062.9  124.61  6182.9  125.74
  6212.9  126.02  6252.1  126.39  7083.4  134.21
BR D #Mann= 3
  2688.6     .12    4939    .045    5061     .13
BR D Banks=4939,5061
BC Design=,, 0 ,, 0 ,,,,,,
BC HTab HWMax=134.46
BC Use User HTab Curves=0
BC User HTab FreeFlow(D)= 0

Type RM Length L Ch R = 1 ,390421.3,2421.324,2421.324,2421.324
BEGIN DESCRIPTION:
Downstream Section of Bridge/Culvert/Weir
END DESCRIPTION:
XS GIS Cut Line= 6
2108080.13051601499816.9244884232107430.12392969500200.658376678
2106474.69424862500733.2037727942106122.28067773501022.966708871
 2105252.9918695501931.4059138012104689.12615602502542.252103314
#Sta/Elev= 19
  2688.6  128.69  2838.6  120.65  3063.6  121.95  3588.6  121.76  4788.6  113.72
  4803.6  111.76  4818.6  111.87  4848.6  108.97    4939  107.25  4942.5   98.75
  5057.5   98.75    5061  107.25  5510.2  109.81  5720.2  110.93  5735.2  111.87
  5750.2  113.79  5765.2  117.04  5885.2  122.94  7083.4  134.21
#Mann= 3 , 1 , 0
  2688.6     .12       0    4939    .045       0    5061     .13       0
#XS Ineff= 2 , 0
       0    4895     116    5105       0     116
Permanent Ineff=
       F       F
Bank Sta=4939,5061
XS Rating Curve= 0 ,0
Exp/Cntr=0.5,0.3

Type RM Length L Ch R = 1 ,388000.0,2000.02,2000.02,2000.02
BEGIN DESCRIPTION:
South River 194.0
END DESCRIPTION:
XS GIS Cut Line= 3
2105737.76678157499687.4331763282104163.70083205499749.393804156
2103431.12340907499969.756037017
#Sta/Elev= 16
  3424.7  124.76  3604.7  122.69  3949.7  115.38  4189.7   115.3  4204.7  114.68
  4219.7   112.8  4249.7  110.56  4951.1  107.26  4955.6   98.26  5044.4   98.26
  5048.9  107.26    5690   110.1    5705  111.92    5720  118.26    5735  121.16
    5765  125.85
#Mann= 3 , 1 , 0
  3424.7     .14       0  4951.1    .045       0  5048.9     .13       0
Bank Sta=4951.1,5048.9
XS Rating Curve= 0 ,0
Exp/Cntr=0.3,0.1

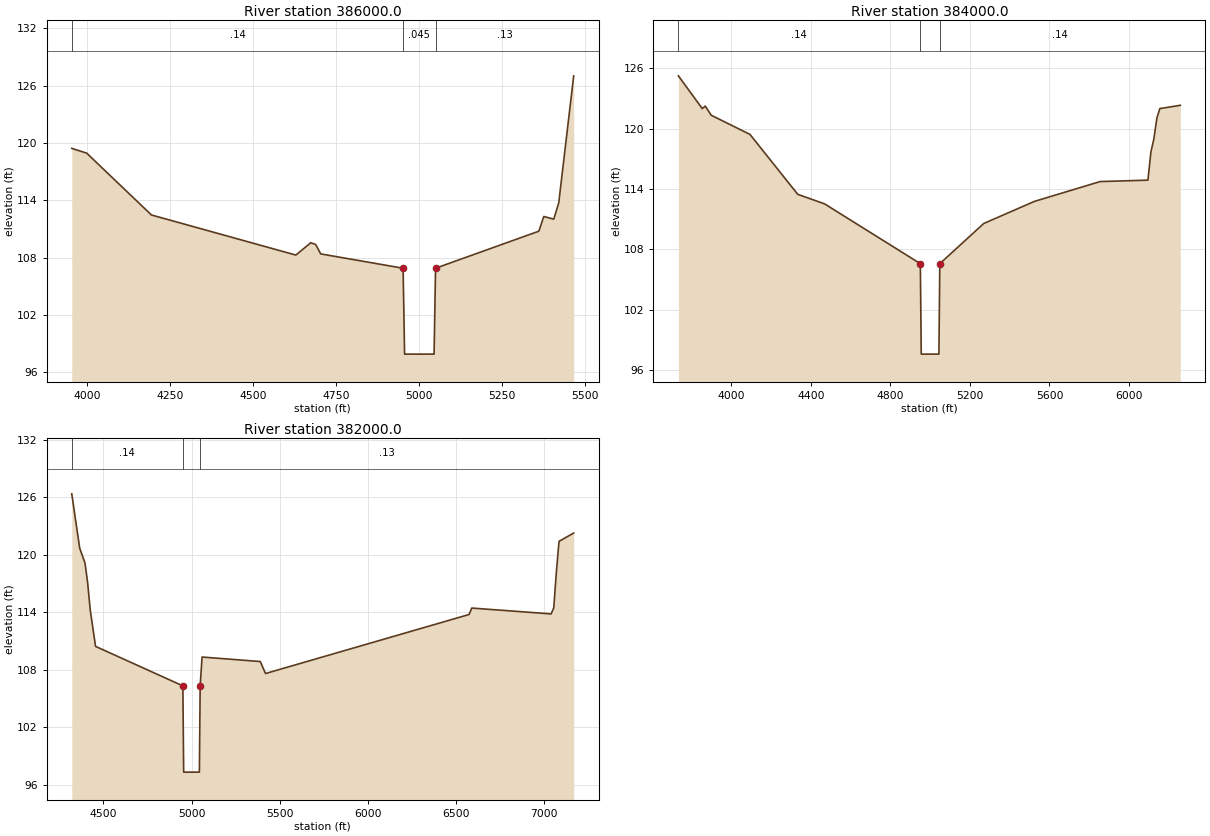
Type RM Length L Ch R = 1 ,386000.0,2000.02,2000.02,2000.02
BEGIN DESCRIPTION:
South River 193.0
END DESCRIPTION:
XS GIS Cut Line= 3
2104729.58656599498884.6150416232104086.26004737498058.576671635
2103829.33744405497670.982744267
#Sta/Elev= 16
    3953  119.44    3998  118.94    4193  112.46    4628  108.26    4673  109.55
    4688  109.36    4703  108.38  4951.1  106.88  4955.6   97.88  5044.4   97.88
  5048.9  106.88    5360  110.76    5375   112.3    5405  112.02    5420  113.74
    5465  127.04
#Mann= 3 , 1 , 0
    3953     .14       0  4951.1    .045       0  5048.9     .13       0
Bank Sta=4951.1,5048.9
XS Rating Curve= 0 ,0
Exp/Cntr=0.3,0.1

Type RM Length L Ch R = 1 ,384000.0,2000.02,2000.02,2000.02
BEGIN DESCRIPTION:
South River 192.0
END DESCRIPTION:
XS GIS Cut Line= 3
2105833.31774976499754.3138540092105964.29907695498495.911103008
2105307.80242487497422.930230829
#Sta/Elev= 20
  3734.8  125.25  3854.8  121.99  3869.8  122.24  3899.8  121.33  4094.8  119.42
  4334.8  113.46  4469.8  112.51  4951.1  106.56  4955.6   97.56  5044.4   97.56
  5048.9  106.56    5270  110.56    5525  112.76    5855  114.73    6095  114.87
    6110  117.66    6125  118.98    6140  121.04    6155  121.99  6257.9  122.32
#Mann= 3 , 1 , 0
  3734.8     .14       0  4951.1    .045       0  5048.9     .14       0
Bank Sta=4951.1,5048.9
XS Rating Curve= 0 ,0
Exp/Cntr=0.3,0.1

Type RM Length L Ch R = 1 ,382000.0,2000.02,2000.02,2000.02
BEGIN DESCRIPTION:
South River 191.0
END DESCRIPTION:
XS GIS Cut Line= 3
2107793.37761043498806.3042481242107303.12264283498335.939482065
2105336.46271528497422.930230829
#Sta/Elev= 20
  4320.6  126.35  4365.6  120.68  4395.6  119.14  4410.6   117.1  4425.6   114.2
  4455.6  110.43    4951  106.31  4955.5   97.31  5044.6   97.31  5049.1  106.31
    5060  109.32    5390  108.85    5420   107.6    6575  113.76    6590  114.43
    7040  113.82    7055  114.43    7070  118.18    7085  121.39  7168.3  122.26
#Mann= 3 , 1 , 0
  4320.6     .14       0    4951    .045       0  5049.1     .13       0
Bank Sta=4951,5049.1
XS Rating Curve= 0 ,0
Exp/Cntr=0.3,0.1