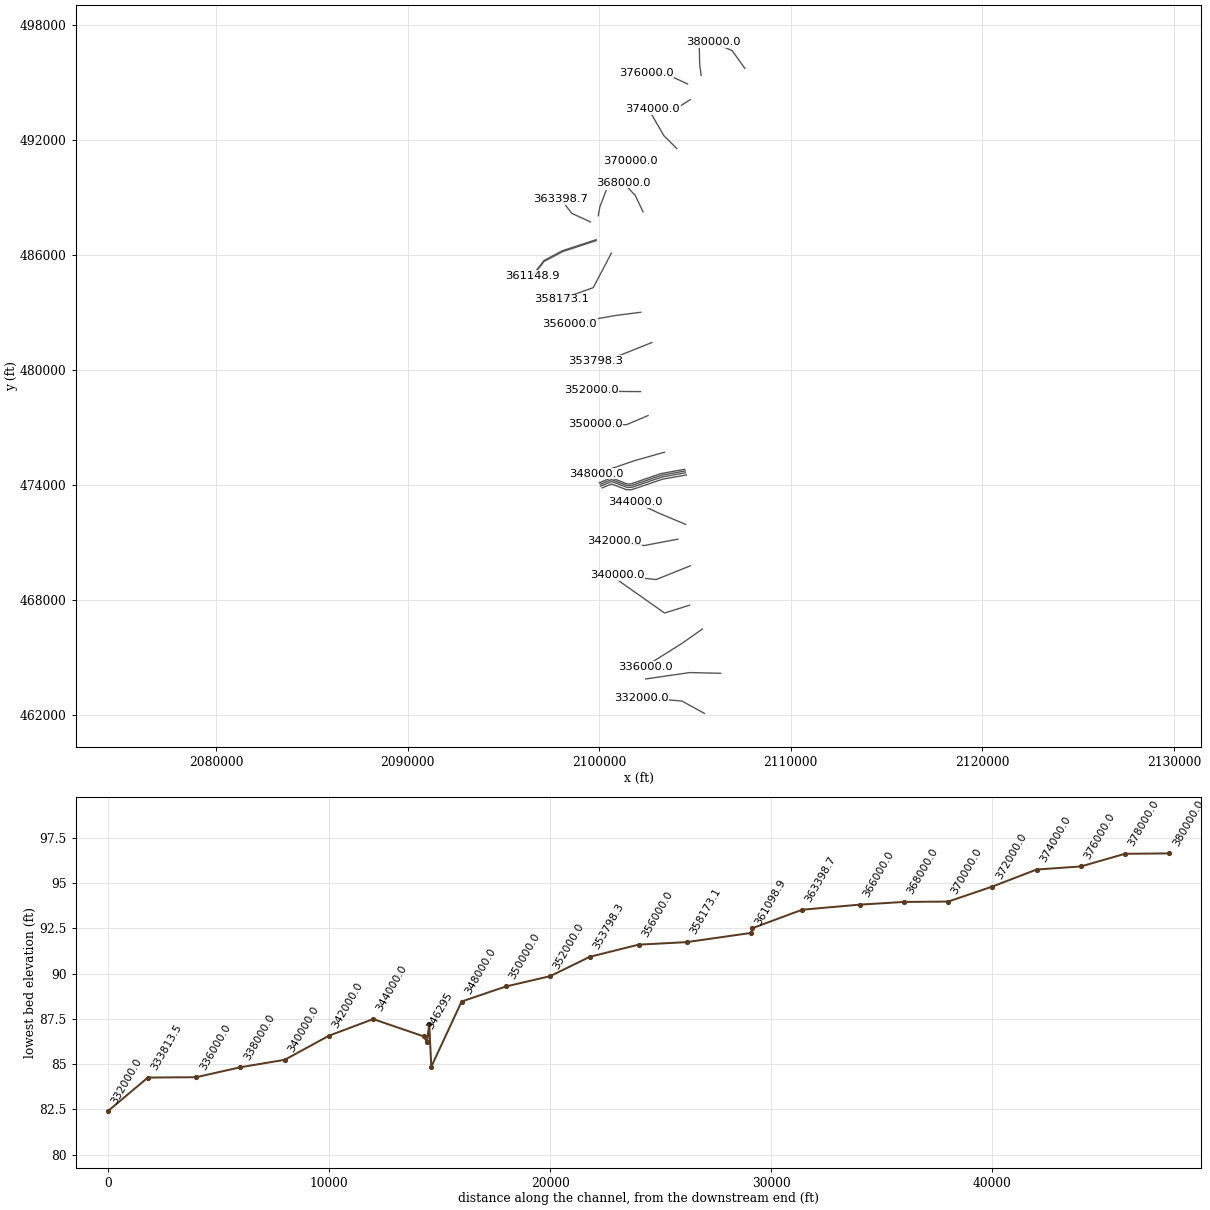
HEC-RAS study B4950SOUTHRIVERS.prj: B4950 SOUTH RIVER SR1851

--- B4950SOUTHRIVERS.g03 (geometry) --- (continued)

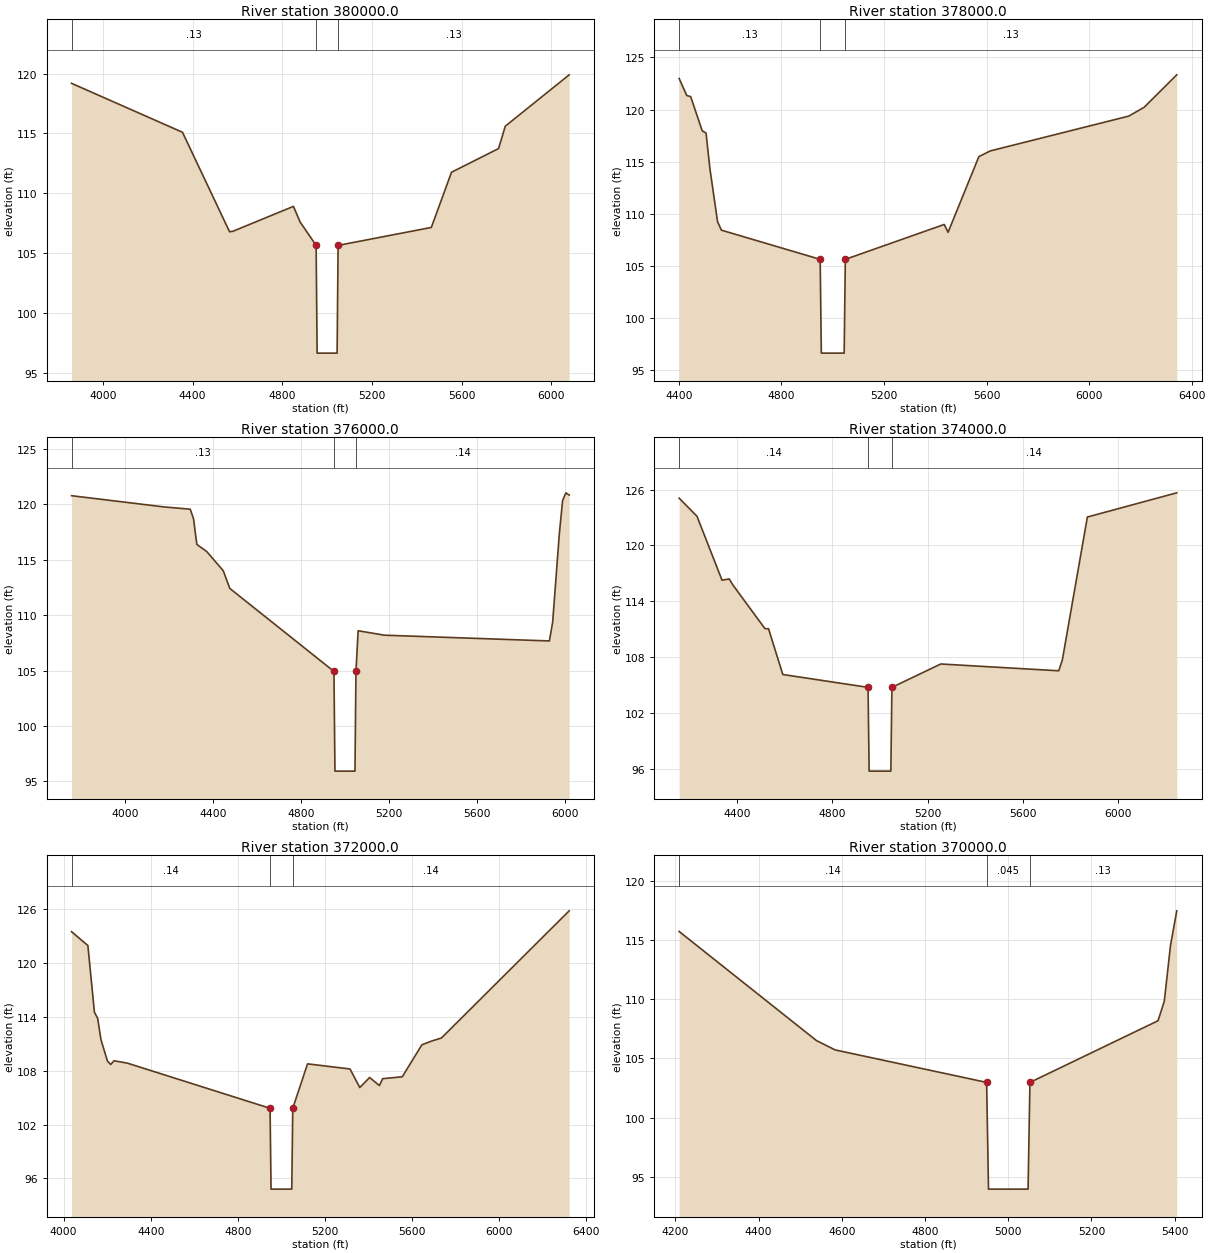
Type RM Length L Ch R = 1 ,380000.0,2000.02,2000.02,2000.02
BEGIN DESCRIPTION:
South River 190.0
END DESCRIPTION:
XS GIS Cut Line= 3
2107600.96566078495731.733094457 2106937.6789399496659.202492214
2105946.14889304497087.356830568
#Sta/Elev= 15
  3859.8  119.18  4354.8  115.09  4564.8  106.78  4579.8  106.82  4849.8   108.9
  4879.8  107.59    4951  105.64  4955.5   96.64  5044.6   96.64  5049.1  105.64
    5465  107.14    5555  111.75    5765  113.73    5795   115.6    6080  119.89
#Mann= 3 , 1 , 0
  3859.8     .13       0    4951    .045       0  5049.1     .13       0
Bank Sta=4951,5049.1
XS Rating Curve= 0 ,0
Exp/Cntr=0.3,0.1

Type RM Length L Ch R = 1 ,378000.0,2000.02,2000.02,2000.02
BEGIN DESCRIPTION:
South River 189.0
END DESCRIPTION:
XS GIS Cut Line= 3
2105319.77254616495362.7093552552105244.26178104495957.135378388
2105212.25145668497298.718972235
#Sta/Elev= 19
  4400.8  122.98  4430.8  121.34  4445.8  121.24  4490.8  117.96  4505.8  117.74
  4520.8  114.34  4550.8  109.22  4565.8  108.42    4951  105.62  4955.5   96.62
  5044.6   96.62  5049.1  105.62    5435  108.97    5450  108.22    5570  115.48
    5615  116.03    6155  119.37    6215  120.22    6342  123.33
#Mann= 3 , 1 , 0
  4400.8     .13       0    4951    .045       0  5049.1     .13       0
Bank Sta=4951,5049.1
XS Rating Curve= 0 ,0
Exp/Cntr=0.3,0.1

Type RM Length L Ch R = 1 ,376000.0,2000.02,2000.02,2000.02
BEGIN DESCRIPTION:
South River 188.0
END DESCRIPTION:
XS GIS Cut Line= 3
2104610.29535725494919.5648650112103481.15391602495440.980148349
2102463.33360276 495507.71082451
#Sta/Elev= 20
  3756.3  120.78  4176.3  119.77  4296.3  119.56  4311.3  118.69  4326.3  116.38
  4371.3  115.74  4446.3  114.01  4476.3  112.41    4950  104.92  4954.5   95.92
  5045.6   95.92  5050.1  104.92    5060  108.59    5180  108.19    5930  107.67
    5945  109.38    5975  117.29    5990  120.33    6005  121.04    6020  120.84
#Mann= 3 , 1 , 0
  3756.3     .13       0    4950    .045       0  5050.1     .14       0
Bank Sta=4950,5050.1
XS Rating Curve= 0 ,0
Exp/Cntr=0.3,0.1

Type RM Length L Ch R = 1 ,374000.0,2000.02,2000.02,2000.02
BEGIN DESCRIPTION:
South River 187.0
END DESCRIPTION:
XS GIS Cut Line= 3
2104751.05678354494098.8165486252104040.07957943 493646.40196445
2102795.57696928493610.841604128
#Sta/Elev= 17
  4157.3  125.08  4232.3  123.13  4337.3  116.26  4367.3   116.4  4382.3  115.77
  4517.3  111.06  4532.3  111.05  4592.3  106.13  4949.9  104.75  4954.4   95.75
  5045.5   95.75    5050  104.75    5255  107.26    5750  106.53    5765  107.69
    5870  123.05    6245  125.65
#Mann= 3 , 1 , 0
  4157.3     .14       0  4949.9    .045       0    5050     .14       0
Bank Sta=4949.9,5050
XS Rating Curve= 0 ,0
Exp/Cntr=0.3,0.1

Type RM Length L Ch R = 1 ,372000.0,2000.02,2000.02,2000.02
BEGIN DESCRIPTION:
South River 186.0
END DESCRIPTION:
XS GIS Cut Line= 3
2104048.92966911491544.5206667452103367.81276757492226.307575078
2102708.88609087493371.689180871
#Sta/Elev= 25
  4036.3  123.48  4081.3  122.55  4111.3  121.94  4141.3  114.52  4156.3  113.82
  4171.3  111.46  4201.3  109.06  4216.3  108.69  4231.3   109.1  4291.3  108.85
  4947.9  103.81  4952.4   94.81  5047.6   94.81  5052.1  103.81    5120  108.76
    5315  108.19    5360  106.12    5405  107.24    5450  106.34    5465  107.11
    5555  107.32    5645  110.88    5690   111.3    5735  111.64  6321.4   125.8
#Mann= 3 , 1 , 0
  4036.3     .14       0  4947.9    .045       0  5052.1     .14       0
Bank Sta=4947.9,5052.1
XS Rating Curve= 0 ,0
Exp/Cntr=0.3,0.1

Type RM Length L Ch R = 1 ,370000.0,2000.02,2000.02,2000.02
BEGIN DESCRIPTION:
South River 185.0
END DESCRIPTION:
XS GIS Cut Line= 3
2102813.98715582490839.6535245472102030.77921982490951.464657494
2101632.04517958490880.463938066
#Sta/Elev= 11
  4208.9  115.71  4538.9  106.51  4583.9  105.72    4948  102.98  4952.5   93.98
  5047.6   93.98  5052.1  102.98    5360  108.18    5375  109.82    5390  114.54
    5405  117.45
#Mann= 3 , 1 , 0
  4208.9     .14       0    4948    .045       0  5052.1     .13       0
Bank Sta=4948,5052.1
XS Rating Curve= 0 ,0
Exp/Cntr=0.3,0.1

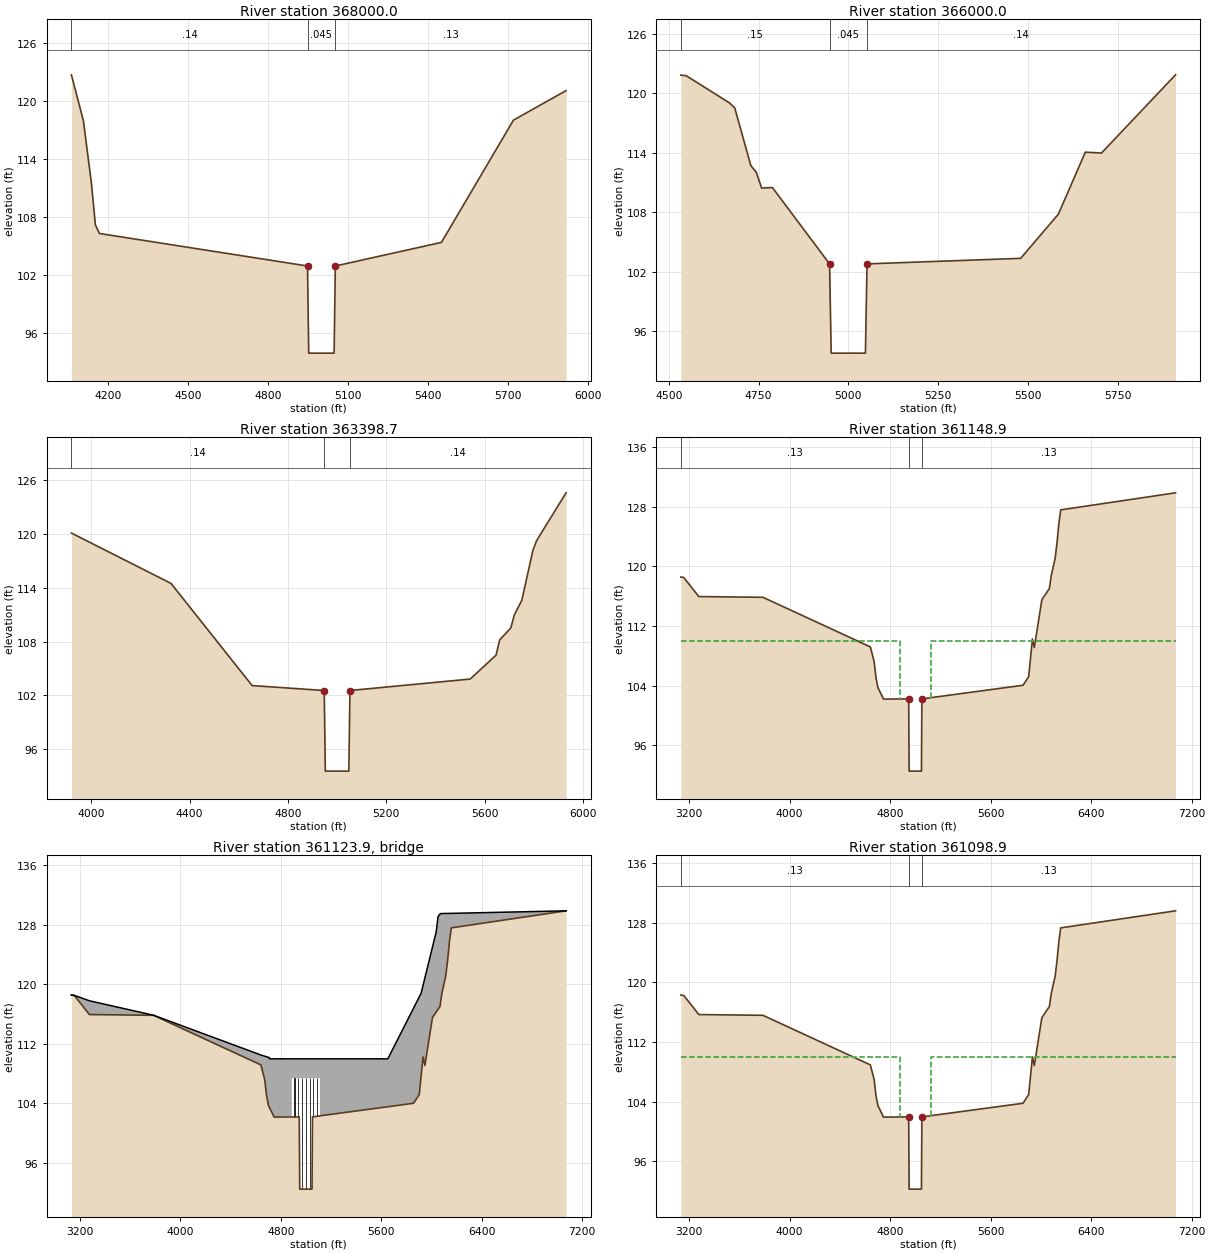
Type RM Length L Ch R = 1 ,368000.0,2000.02,2000.02,2000.02
BEGIN DESCRIPTION:
South River 184.0
END DESCRIPTION:
XS GIS Cut Line= 3
2102285.08179659488244.1672252962101885.31774591489092.065816787
2101256.55137481489759.962584376
#Sta/Elev= 12
  4062.6  122.71  4107.6  117.97  4137.6  111.51  4152.6  107.21  4167.6  106.32
  4947.9  102.96  4952.4   93.96  5047.6   93.96  5052.1  102.96    5450   105.4
    5720  118.03  5917.3  121.08
#Mann= 3 , 1 , 0
  4062.6     .14       0  4947.9    .045       0  5052.1     .13       0
Bank Sta=4947.9,5052.1
XS Rating Curve= 0 ,0
Exp/Cntr=0.3,0.1

Type RM Length L Ch R = 1 ,366000.0,2601.326,2601.326,2601.326
BEGIN DESCRIPTION:
South River 183.0
END DESCRIPTION:
XS GIS Cut Line= 3
2099951.55815173488039.3751502022100031.41896093488498.789805307
2100358.40227415489349.098421218
#Sta/Elev= 17
  4533.7  121.85  4548.7  121.79  4668.7  119.06  4683.7  118.56  4728.7  112.72
  4743.7  112.06  4758.7  110.46  4788.7  110.51  4947.9  102.81  4952.4   93.81
  5047.7   93.81  5052.2  102.81    5480  103.37    5585  107.83    5660  114.08
    5705  113.99  5911.1  121.88
#Mann= 3 , 1 , 0
  4533.7     .15       0  4947.9    .045       0  5052.2     .14       0
Bank Sta=4947.9,5052.2
XS Rating Curve= 0 ,0
Exp/Cntr=0.3,0.1

Type RM Length L Ch R = 1 ,363398.7,2249.823,2249.823,2249.823
BEGIN DESCRIPTION:
South River 182.0
END DESCRIPTION:
XS GIS Cut Line= 3
 2099546.2340447487715.2218656592098562.08407262488164.296415991
2098004.07841852488908.303954786
#Sta/Elev= 16
  3919.5  120.11  4324.5  114.49  4654.5  103.08  4947.7  102.53  4952.2   93.53
  5047.8   93.53  5052.3  102.53  5541.3  103.81  5646.3  106.47  5661.3  108.18
  5706.3  109.51  5721.3     111  5751.3  112.61  5796.3  118.16  5811.3  119.26
  5931.3   124.6
#Mann= 3 , 1 , 0
  3919.5     .14       0  4947.7    .045       0  5052.3     .14       0
Bank Sta=4947.7,5052.3
XS Rating Curve= 0 ,0
Exp/Cntr=0.5,0.3

Type RM Length L Ch R = 1 ,361148.9,50.0005,50.0005,50.0005
BEGIN DESCRIPTION:
Upstream Section of Bridge/Culvert/Weir
END DESCRIPTION:
XS GIS Cut Line= 4
2099838.59700713486788.1224716512098091.35930291486217.136686031
2097120.66946722485703.2414788912096503.99321863484915.263494557
#Sta/Elev= 25
    3134  118.57  3157.5  118.51  3277.5  115.95  3787.5  115.85  4642.5  109.19
  4672.5  107.22  4687.5  105.03  4702.5  103.73  4747.5  102.18  4947.5  102.21
    4951   92.51    5049   92.51  5052.5  102.21  5857.4  104.04  5902.4  105.19
  5932.4  110.26  5947.4  109.11  6007.4  115.53  6067.4  117.03  6082.4   118.8
  6112.4  121.02  6127.4  123.08  6142.4  125.68  6157.4  127.59  7071.1  129.88
#Mann= 3 , 1 , 0
    3134     .13       0  4947.5    .045       0  5052.5     .13       0
#XS Ineff= 2 , 0
       0    4875     110    5125       0     110
Permanent Ineff=
       F       F
Bank Sta=4947.5,5052.5
XS Rating Curve= 0 ,0
Exp/Cntr=0.5,0.3

Type RM Length L Ch R = 3 ,361123.9,,,
BEGIN DESCRIPTION:
Maxwell Rd-TOR
Structure ID: HLS-0493
Approximate Survey Structure
END DESCRIPTION:
Bridge Culvert--1,0,-1,-1, 0
Deck Dist Width WeirC Skew NumUp NumDn MinLoCord MaxHiCord MaxSubmerge Is_Ogee
10,30,2.6,0, 39, 39, , , 0.95, 0, 1,1,,
    3134  3157.5  3277.5  3787.5  4642.5  4672.5  4687.5  4702.5    4709  4709.9
  4747.5 4887.91    4888    4895  4947.5    4951    5000    5049  5052.5    5105
 5111.89    5112  5652.4  5857.4  5902.4  5917.2  5932.4  5947.4  6007.4  6037.2
  6052.2  6067.4  6070.5  6082.4  6112.4  6127.4  6142.4  6157.4  7071.1
  118.56  118.51  117.79  115.85  110.51  110.35  110.27  110.19  110.16     110
     110     110     110     110     110     110     110     110     110     110
     110     110     110  116.81  118.31   118.8  119.84  120.87  124.99  127.03
  129.11  129.43   129.5   129.5  129.52  129.52  129.53  129.53  129.87
  118.56   118.5  115.94  115.84  109.18  107.21  105.02  103.72   103.5  103.47
  102.17  102.19   107.4   107.4   107.4   107.4   107.4   107.4   107.4   107.4
   107.4  102.34  103.56  104.03  105.18  107.68  110.25   109.1  115.52  116.27
  116.64  117.02  117.39  118.79  121.01  123.07  125.67  127.58  129.87
    3134  3157.5  3277.5  3787.5  4642.5  4672.5  4687.5  4702.5    4709  4709.9
  4747.5 4887.91    4888    4895  4947.5    4951    5000    5049  5052.5    5105
 5111.89    5112  5652.4  5857.4  5902.4  5917.2  5932.4  5947.4  6007.4  6037.2
  6052.2  6067.4  6070.5  6082.4  6112.4  6127.4  6142.4  6157.4  7071.1
  118.56  118.51  117.79  115.85  110.51  110.35  110.27  110.19  110.16     110
     110     110     110     110     110     110     110     110     110     110
     110     110     110  116.81  118.31   118.8  119.84  120.87  124.99  127.03
  129.11  129.43   129.5   129.5  129.52  129.52  129.53  129.53  129.87
  118.31  118.25  115.69  115.59  108.93  106.96  104.77  103.47  103.25  103.22
  101.92  101.94  107.15  107.15  107.15  107.15  107.15  107.15  107.15  107.15
  107.15  102.09  103.31  103.78  104.93  107.43     110  108.85  115.27  116.02
  116.39  116.77  117.14  118.54  120.76  122.82  125.42  127.33  129.62
Pier Skew, UpSta & Num, DnSta & Num=  ,4910, 2 ,4910, 2 , 0 , 0 , 0 ,,
       1       1
  101.19   108.4
       1       1
  100.94  108.15
Pier Skew, UpSta & Num, DnSta & Num=  ,4940, 2 ,4940, 2 , 0 , 0 , 0 ,,
       1       1
   101.2   108.4
       1       1
  100.95  108.15
Pier Skew, UpSta & Num, DnSta & Num=  ,4970, 2 ,4970, 2 , 0 , 0 , 0 ,,
       1       1
    91.5   108.4
       1       1
   91.25  108.15
Pier Skew, UpSta & Num, DnSta & Num=  ,5000, 2 ,5000, 2 , 0 , 0 , 0 ,,
       1       1
    91.5   108.4
       1       1
   91.25  108.15
Pier Skew, UpSta & Num, DnSta & Num=  ,5030, 2 ,5030, 2 , 0 , 0 , 0 ,,
       1       1
    91.5   108.4
       1       1
   91.25  108.15
Pier Skew, UpSta & Num, DnSta & Num=  ,5060, 2 ,5060, 2 , 0 , 0 , 0 ,,
       1       1
  101.22   108.4
       1       1
  100.97  108.15
Pier Skew, UpSta & Num, DnSta & Num=  ,5090, 2 ,5090, 2 , 0 , 0 , 0 ,,
       1       1
  101.28   108.4
       1       1
  101.03  108.15
Abutment Skew #Up #Dn= , 2 , 2
  4887.8    4895
   107.4  102.19
  4887.8    4895
  107.15  101.94
Abutment Skew #Up #Dn= , 2 , 2
    5105 5112.09
  102.32   107.4
    5105 5112.09
  102.07  107.15
BR Coef= 1 , 1 , 0 ,1.25, 0 ,,,0.8,0,2,0,
WSPro=,,,, 1 ,,,, 0 ,,,, 0 ,,,,-1 ,-1 ,-1 , 0 , 0 , 0 , 0 , 0
BR U #Sta/Elev= 39
    3134  118.56  3157.5   118.5  3277.5  115.94  3787.5  115.84  4642.5  109.18
  4672.5  107.21  4687.5  105.02  4702.5  103.72    4709   103.5  4709.9  103.47
  4747.5  102.17 4887.91  102.19    4888  102.19    4895  102.19  4947.5   102.2
    4951    92.5    5000    92.5    5049    92.5  5052.5   102.2    5105  102.32
 5111.89  102.34    5112  102.34  5652.4  103.56  5857.4  104.03  5902.4  105.18
  5917.2  107.68  5932.4  110.25  5947.4   109.1  6007.4  115.52  6037.2  116.27
  6052.2  116.64  6067.4  117.02  6070.5  117.39  6082.4  118.79  6112.4  121.01
  6127.4  123.07  6142.4  125.67  6157.4  127.58  7071.1  129.87
BR U #Mann= 3
    3134     .13  4947.5    .045  5052.5     .13
BR U Banks=4947.5,5052.5
BR D #Sta/Elev= 39
    3134  118.31  3157.5  118.25  3277.5  115.69  3787.5  115.59  4642.5  108.93
  4672.5  106.96  4687.5  104.77  4702.5  103.47    4709  103.25  4709.9  103.22
  4747.5  101.92 4887.91  101.94    4888  101.94    4895  101.94  4947.5  101.95
    4951   92.25    5000   92.25    5049   92.25  5052.5  101.95    5105  102.07
 5111.89  102.09    5112  102.09  5652.4  103.31  5857.4  103.78  5902.4  104.93
  5917.2  107.43  5932.4     110  5947.4  108.85  6007.4  115.27  6037.2  116.02
  6052.2  116.39  6067.4  116.77  6070.5  117.14  6082.4  118.54  6112.4  120.76
  6127.4  122.82  6142.4  125.42  6157.4  127.33  7071.1  129.62
BR D #Mann= 3
    3134     .13  4947.5    .045  5052.5     .13
BR D Banks=4947.5,5052.5
BC Design=,, 0 ,, 0 ,,,,,,
BC HTab HWMax=129.88
BC Use User HTab Curves=0
BC User HTab FreeFlow(D)= 0

Type RM Length L Ch R = 1 ,361098.9,2925.83,2925.83,2925.83
BEGIN DESCRIPTION:
Downstream Section of Bridge/Culvert/Weir
END DESCRIPTION:
XS GIS Cut Line= 4
2099838.59700713486738.1219650112098091.35930291486167.136179391
2097120.66946722485653.2409722522096503.99321863484865.262987918
#Sta/Elev= 25
    3134  118.31  3157.5  118.25  3277.5  115.69  3787.5  115.59  4642.5  108.93
  4672.5  106.96  4687.5  104.77  4702.5  103.47  4747.5  101.92  4947.5  101.95
    4951   92.25    5049   92.25  5052.5  101.95  5857.4  103.78  5902.4  104.93
  5932.4     110  5947.4  108.85  6007.4  115.27  6067.4  116.77  6082.4  118.54
  6112.4  120.76  6127.4  122.82  6142.4  125.42  6157.4  127.33  7071.1  129.62
#Mann= 3 , 1 , 0
    3134     .13       0  4947.5    .045       0  5052.5     .13       0
#XS Ineff= 2 , 0
       0    4875     110    5125       0     110
Permanent Ineff=
       F       F
Bank Sta=4947.5,5052.5
XS Rating Curve= 0 ,0
Exp/Cntr=0.5,0.3

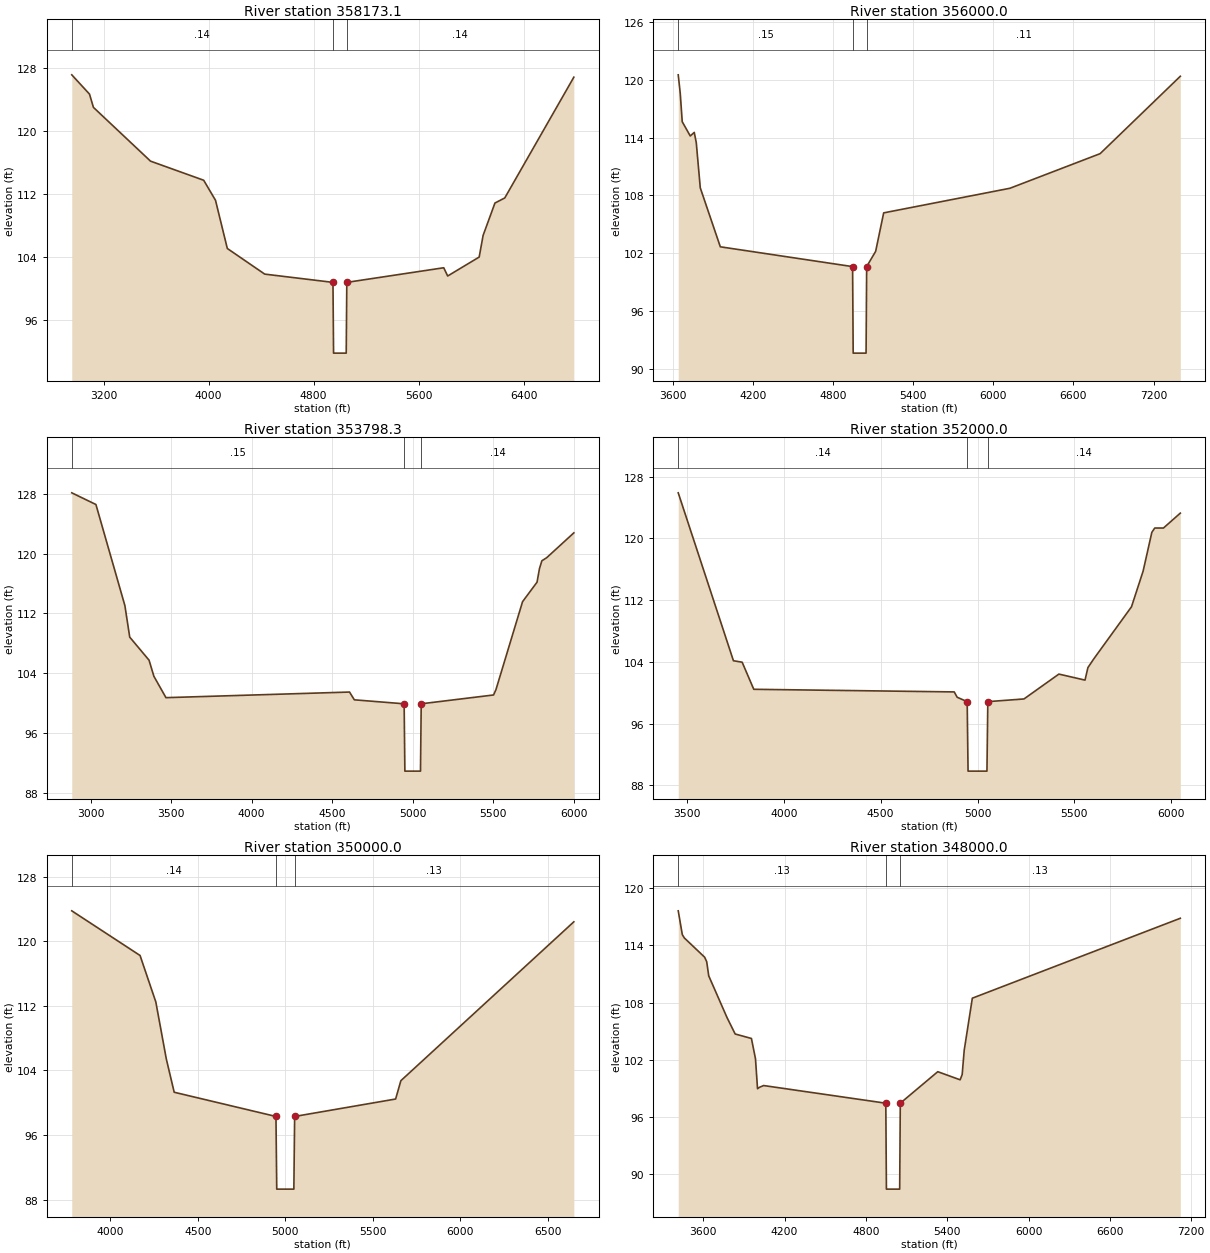
Type RM Length L Ch R = 1 ,358173.1,2173.122,2173.122,2173.122
BEGIN DESCRIPTION:
South River 179.0
END DESCRIPTION:
XS GIS Cut Line= 3
2100635.48508174486090.9054069692099689.55549694 484285.03710867
2098007.90845733483683.081009238
#Sta/Elev= 19
  2957.5  127.14  3092.5  124.69  3122.5     123  3557.5  116.16  3962.5  113.73
  4052.5  111.18  4142.5  105.05  4427.5  101.79  4947.3  100.74  4951.8   91.74
  5048.2   91.74  5052.7  100.74  5791.1   102.6  5821.1  101.55  6061.1  103.96
  6091.1  106.72  6181.1  110.83  6256.1  111.48  6782.2  126.84
#Mann= 3 , 1 , 0
  2957.5     .14       0  4947.3    .045       0  5052.7     .14       0
Bank Sta=4947.3,5052.7
XS Rating Curve= 0 ,0
Exp/Cntr=0.3,0.1

Type RM Length L Ch R = 1 ,356000.0,2201.722,2201.722,2201.722
BEGIN DESCRIPTION:
South River 178.0
END DESCRIPTION:
XS GIS Cut Line= 3
2102166.03059028482999.0340780042100819.44694577482826.372328477
2098456.98300766482402.738035923
#Sta/Elev= 17
  3642.4  120.55  3657.4  118.63  3672.4  115.67  3732.4  114.19  3762.4  114.56
  3777.4   113.5  3807.4  108.79  3957.4  102.66  4947.3   100.6  4951.8    91.6
  5048.2    91.6  5052.7   100.6    5120  102.19    5180  106.19    6125  108.75
    6800  112.35  7400.1   120.4
#Mann= 3 , 1 , 0
  3642.4     .15       0  4947.3    .045       0  5052.7     .11       0
Bank Sta=4947.3,5052.7
XS Rating Curve= 0 ,0
Exp/Cntr=0.3,0.1

Type RM Length L Ch R = 1 ,353798.3,1798.318,1798.318,1798.318
BEGIN DESCRIPTION:
South River 177.0
END DESCRIPTION:
XS GIS Cut Line= 3
2102747.10647814 481418.588063842100788.36663085  480635.0901249
2099794.66656199480463.108382263
#Sta/Elev= 21
  2882.8  128.13  3032.8  126.57  3212.8  113.05  3242.8  108.84  3362.8  105.76
  3392.8  103.61  3467.8  100.75  4607.8   101.5  4637.8  100.46    4947   99.93
  4951.5   90.93  5048.5   90.93    5053   99.93  5502.4  101.11  5517.4  101.84
  5682.4  113.58  5772.4  116.19  5787.4     118  5802.4  119.05  5832.4  119.46
  6000.9  122.78
#Mann= 3 , 1 , 0
  2882.8     .15       0    4947    .045       0    5053     .14       0
Bank Sta=4947,5053
XS Rating Curve= 0 ,0
Exp/Cntr=0.3,0.1

Type RM Length L Ch R = 1 ,352000.0,2000.02,2000.02,2000.02
BEGIN DESCRIPTION:
South River 176.0
END DESCRIPTION:
XS GIS Cut Line= 3
2102154.71047558478857.8921171092100609.64481991 478868.21222168
2099565.34423834478943.882988428
#Sta/Elev= 21
  3454.9  125.91  3739.9  104.16  3784.9  103.97  3844.9  100.46  4879.9  100.12
  4894.9   99.43  4946.7   98.86  4951.2   89.86  5048.7   89.86  5053.2   98.86
    5240   99.21    5420  102.43    5555  101.65    5570  103.27    5600  104.39
    5795  111.15    5855  115.77    5900  120.79    5915  121.35    5960  121.35
    6047  123.28
#Mann= 3 , 1 , 0
  3454.9     .14       0  4946.7    .045       0  5053.2     .14       0
Bank Sta=4946.7,5053.2
XS Rating Curve= 0 ,0
Exp/Cntr=0.3,0.1

Type RM Length L Ch R = 1 ,350000.0,2000.02,2000.02,2000.02
BEGIN DESCRIPTION:
South River 175.0
END DESCRIPTION:
XS GIS Cut Line= 3
  2102546.454445477606.2094342012101423.31306456477130.874617782
2099775.55636836477157.134883869
#Sta/Elev= 12
  3780.4  123.76  4170.4  118.23  4260.4  112.48  4320.4  105.41  4365.4  101.29
  4946.6   98.29  4951.1   89.29  5048.8   89.29  5053.3   98.29    5630  100.45
    5660  102.72  6647.9   122.4
#Mann= 3 , 1 , 0
  3780.4     .14       0  4946.6    .045       0  5053.3     .13       0
Bank Sta=4946.6,5053.3
XS Rating Curve= 0 ,0
Exp/Cntr=0.3,0.1

Type RM Length L Ch R = 1 ,348000.0,1370.7,1370.7,1370.7
BEGIN DESCRIPTION:
South River 174.0
END DESCRIPTION:
XS GIS Cut Line= 3
2103393.31302595475690.3500213972101868.18757233475259.475655482
2099861.54723967474577.328743501
#Sta/Elev= 23
  3415.2  117.61  3445.2  115.12  3460.2  114.77  3610.2  112.75  3625.2  112.28
  3640.2   110.8  3775.2  106.43  3835.2  104.71  3955.2  104.24  3985.2  102.11
  4000.2   98.98  4015.2   99.13  4045.2   99.31  4946.6   97.46  4951.1   88.46
    5049   88.46  5053.5   97.46    5330  100.76    5495   99.91    5510  100.46
    5525     103    5585  108.46  7119.4  116.83
#Mann= 3 , 1 , 0
  3415.2     .13       0  4946.6    .045       0  5053.5     .13       0
Bank Sta=4946.6,5053.5
XS Rating Curve= 0 ,0
Exp/Cntr=0.3,0.1

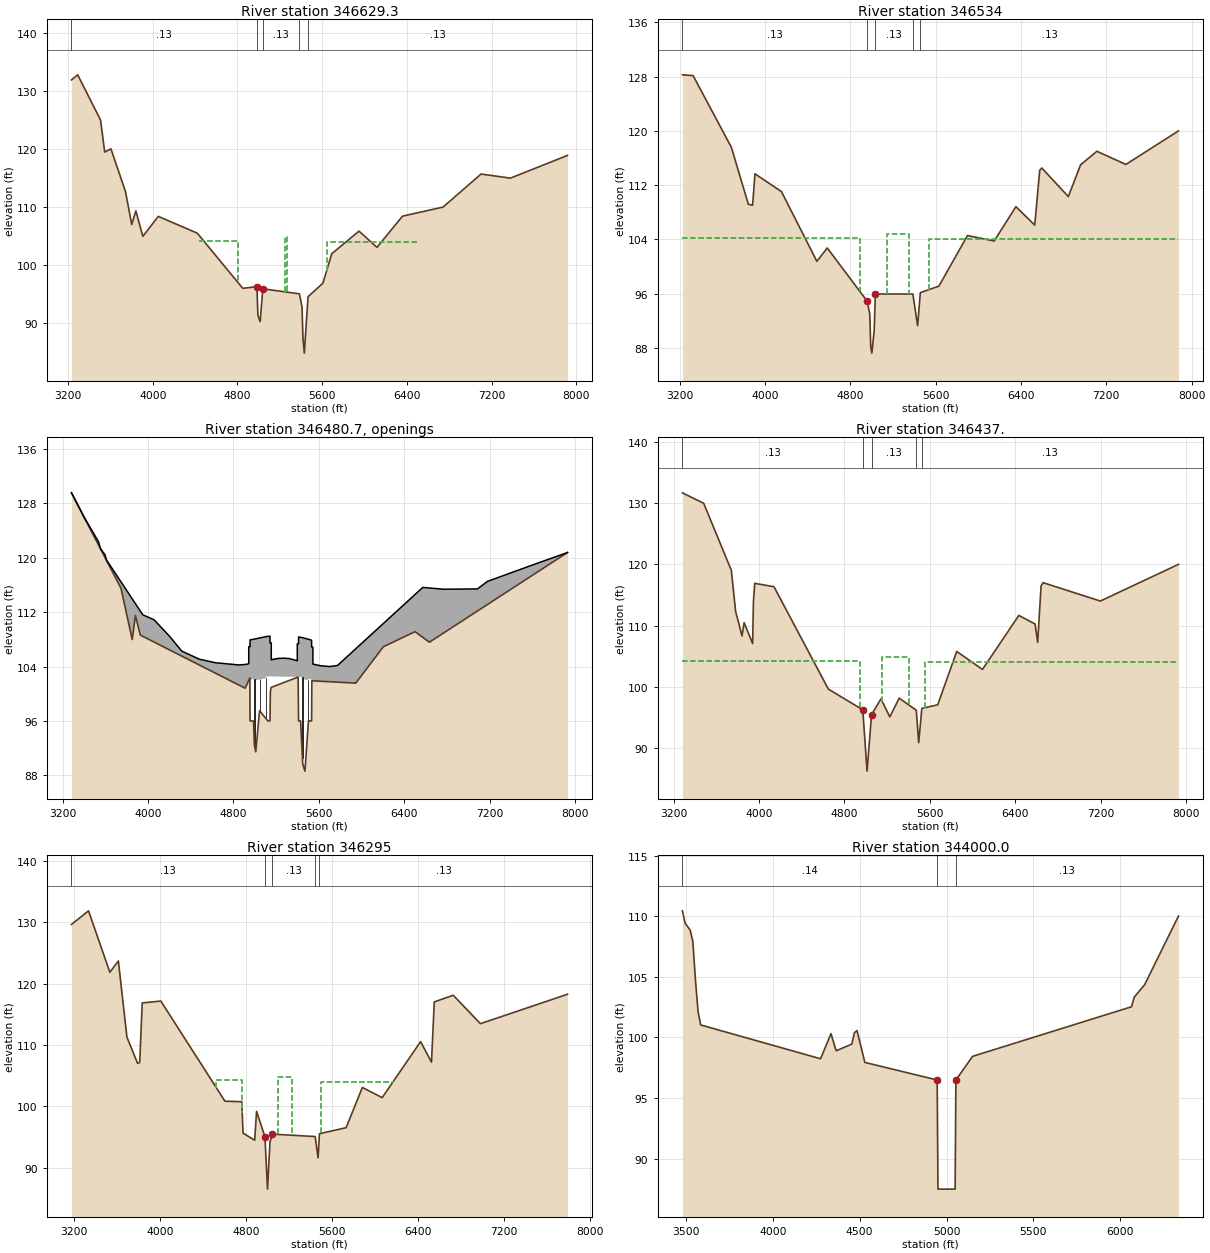
Type RM Length L Ch R = 1 ,346629.3,95.3,95.3,95.3
XS GIS Cut Line= 6
2104463.28293052474801.5572039192103232.83001086474580.755152091
2101653.82726339474040.8211925772101468.35519338474034.642399162
2100631.11474186474359.234597757 2100005.6451923474097.960185915
#Sta/Elev= 30
  3233.1  131.91 3291.93  132.79 3507.65     125 3546.87  119.49  3605.7  120.04
 3742.98  112.69 3801.81  107.02 3841.03  109.35    3907  104.97  4052.7  108.41
 4420.55  105.52 4850.02   96.02  4983.5    96.3 4993.15   91.34 5013.96   90.29
 5039.58   95.94 5384.53   95.07 5409.47    92.8 5418.07   87.46  5431.1   84.86
 5466.27   94.58 5606.46    96.9 5689.93  101.97 5947.24  105.87 6117.06  103.07
 6357.73  108.45  6740.4  110.01 7099.06   115.7 7376.92     115 7915.21  118.91
#Mann= 5 ,-1 , 0
  3233.1     .13       0  4983.5    .045       0 5039.58     .13       0
 5384.53    .045       0 5466.27     .13       0
#XS Ineff= 3 ,-1
    4440  4809.1  104.24  5244.1  5267.1  104.85  5641.1    6500  103.99
Permanent Ineff=
       F       F       F
Bank Sta=4983.5,5039.58
XS Rating Curve= 0 ,0
Exp/Cntr=0.5,0.3

Type RM Length L Ch R = 1 ,346534  ,97,97,97
XS GIS Cut Line= 6
2104491.80879211474715.4894626742103273.82336721474497.345870078
2101680.00372019473953.7711698412101463.12685737473946.546118662
2100641.39818588474262.2935186622100058.87802544474018.960015833
#Sta/Elev= 30
 3224.77  128.27 3324.47  128.16 3683.39  117.59 3842.91  109.18 3882.79  109.04
 3905.08  113.67 4153.27  111.05 4485.41  100.76  4583.1  102.73 4957.25   94.89
 4981.33   93.03 4990.45   88.22 5000.98   87.22 5022.72   90.48 5034.11   95.94
 5385.76   95.94 5430.23   91.27 5455.81   96.14 5629.71    97.1 5898.02  104.56
  6148.2  103.76 6352.21  108.82  6528.8  106.11 6575.41  114.19 6594.59  114.53
 6843.83  110.31 6958.81     115  7111.9  116.99 7383.39  115.05  7876.6     120
#Mann= 5 ,-1 , 0
 3224.77     .13       0 4957.25    .045       0 5034.11     .13       0
 5385.76    .045       0 5455.81     .13       0
#XS Ineff= 3 ,-1
 3224.77 4887.77  104.24    5142 5347.77  104.85 5536.77  7876.6  103.99
Permanent Ineff=
       F       F       F
Bank Sta=4957.25,5034.11
XS Rating Curve= 0 ,0
Exp/Cntr=0.5,0.3

Type RM Length L Ch R = 4 ,346480.7,,,
BEGIN DESCRIPTION:
Faircloth Rd-TOR
Structure ID: HLS-0492
Approximate Survey Structure
END DESCRIPTION:
Bridge Culvert--1,0,-1,-1, 0
Deck Dist Width WeirC Skew NumUp NumDn MinLoCord MaxHiCord MaxSubmerge Is_Ogee
33,33,2.6,0, 60, 60, , , 0.98, 0, 1,1,,
  3281.5  3296.5  3326.5  3386.5  3401.5  3536.5  3551.5  3596.5  3611.5  3626.5
3950.1524056.0784199.5344315.7634478.8444628.592  4846.3    4875    4925    4943
    4943    4955    49554996.1254996.1255051.1255106.1255106.125 5142.25 5142.25
 5154.25 5154.25    5175    5225    5275    5325    5398    5398    5410    5410
5446.1255446.1255501.1255501.125 5532.25 5532.25 5544.25 5544.25    5575    5625
    5685  5689.3    5725    57756574.193  6771.7  7086.7  7181.2  7573.2  7930.6
  129.55  129.11   128.2  126.38  125.93  122.31  121.39  120.42  119.58  119.28
 111.609 110.874 108.477 106.268 105.086 104.567  104.24  104.26  104.34  104.42
  106.92  106.92  107.92  108.04  108.04  108.22   108.4   108.4  108.48  107.48
  107.48  104.98  105.08   105.2  105.23  105.17  104.85  107.35  107.35  108.35
  108.25  108.25  108.02  108.02  107.87  106.87  106.87  104.37  104.25   104.1
  104.03  103.99  104.05  104.16 115.641  115.37  115.42  116.53  118.77  120.77
                                                                                
                                                                                
                     102   102.2  101.95  102.12  102.28  102.53  102.55
                                                                          102.48
  102.44  102.19  101.97  102.22  102.08
                                                                                
  3281.5  3296.5  3326.5  3386.5  3401.5  3536.5  3551.5  3596.5  3611.5  3626.5
3950.1524056.0784199.5344315.7634478.8444628.592  4846.3    4875    4925    4943
    4943    4955    49554996.1254996.1255051.1255106.1255106.125 5142.25 5142.25
 5154.25 5154.25    5175    5225    5275    5325    5398    5398    5410    5410
5446.1255446.1255501.1255501.125 5532.25 5532.25 5544.25 5544.25    5575    5625
    5685  5689.3    5725    57756574.193  6771.7  7086.7  7181.2  7573.2  7930.6
  129.55  129.11   128.2  126.38  125.93  122.31  121.39  120.42  119.58  119.28
 111.609 110.874 108.477 106.268 105.086 104.567  104.24  104.26  104.34  104.42
  106.92  106.92  107.92  108.04  108.04  108.22   108.4   108.4  108.48  107.48
  107.48  104.98  105.08   105.2  105.23  105.17  104.85  107.35  107.35  108.35
  108.25  108.25  108.02  108.02  107.87  106.87  106.87  104.37  104.25   104.1
  104.03  103.99  104.05  104.16 115.641  115.37  115.42  116.53  118.77  120.77
                                                                                
                                                                                
                     102   102.2  101.95  102.12  102.28  102.53  102.55
                                                                          102.48
  102.44  102.19  101.97  102.22  102.08
                                                                                
Pier Skew, UpSta & Num, DnSta & Num=  ,4996.125, 2 ,4996.125, 2 , 0 , 0 , 0 ,,
       3       3
    87.1   102.5
       3       3
   86.85  102.25
Pier Skew, UpSta & Num, DnSta & Num=  ,5051.125, 2 ,5051.125, 2 , 0 , 0 , 0 ,,
       3       3
    87.1   102.5
       3       3
   86.85  102.25
Pier Skew, UpSta & Num, DnSta & Num=  ,5106.125, 2 ,5106.125, 2 , 0 , 0 , 0 ,,
       3       3
    87.1  102.66
       3       3
   86.85  102.41
Pier Skew, UpSta & Num, DnSta & Num=  ,5446.125, 2 ,5446.125, 2 , 0 , 0 , 0 ,,
       3       3
    87.1  102.66
       3       3
   86.85  102.41
Pier Skew, UpSta & Num, DnSta & Num=  ,5501.125, 2 ,5501.125, 2 , 0 , 0 , 0 ,,
       3       3
    87.1  102.66
       3       3
   86.85  102.41
Abutment Skew #Up #Dn= , 5 , 5
    4955 4957.75 4957.75 4959.25 4987.85
  101.99  101.99      99      99      96
    4955 4957.75 4957.75 4959.25    4980
  101.99  101.99      99      99      96
Abutment Skew #Up #Dn= , 5 , 5
  5114.3    5138  5139.5  5139.5 5142.25
      96   99.55   99.55  102.55  102.55
  5114.3    5138  5139.5  5139.5 5142.25
      96   99.55   99.55  102.55  102.55
Abutment Skew #Up #Dn= , 5 , 5
    5410 5412.75 5412.75 5414.22    5429
  102.48  102.48   99.48   99.48      96
    5410 5412.75 5412.75 5414.22    5433
  102.48  102.48   99.48   99.48      96
Abutment Skew #Up #Dn= , 5 , 5
 5510.43 5528.03  5529.5  5529.5 5532.25
      96      99      99     102     102
  5513.5 5528.03  5529.5  5529.5 5532.25
      96      99      99     102     102
BR Coef= 1 , 1 , 0 ,0.9, 0 ,,,0.8,0,1.2,0,
WSPro=,,,, 1 ,,,, 0 ,,,, 0 ,,,,-1 ,-1 ,-1 , 0 , 0 , 0 , 0 , 0
BR Coef= 1 , 1 , 0 ,0.9, 0 ,,,0.8,0,1.2,0,
WSPro=,,,, 1 ,,,, 0 ,,,, 0 ,,,,-1 ,-1 ,-1 , 0 , 0 , 0 , 0 , 0
BC Mult= 3 ,3224.77,5200,3282.17,5200
BC Mult= 3 ,5200,7876.6,5200,7928.88
BR U #Sta/Elev= 30
  3281.5  129.55  3745.9   115.5  3850.9  107.97  3880.9   111.5  3926.5  108.63
 4909.39  100.81 4953.78  102.34    4955      96 4987.85      96  4995.8   92.44
  5008.8   91.46 5044.55    97.5 5123.03      96 5142.25      96 5145.64  100.25
 5152.63  100.93 5402.05  102.43 5406.04   102.4    5410      96    5429      96
    5449   89.68  5469.7   88.62  5502.8   96.03 5532.25      96 5534.38  101.91
 5945.94  101.56 6204.72  106.91  6501.5  109.13  6636.5  107.58  7930.6  120.77
BR U #Mann= 5
  3281.5     .13    4955    .045 5123.03     .13    5429    .045 5532.25     .13
BR U Banks=4955,5123.03
BR D #Sta/Elev= 30
  3281.5   129.3  3745.9  115.25  3850.9  107.72  3880.9  111.25  3941.5  107.87
4650.614  105.924804.544   99.634925.774  101.724942.344  100.83    4955      96
    4980      96  4995.7   92.39  5008.6   92.29  5044.4   97.66 5123.03      96
 5142.25      965152.604  100.735184.994  101.275378.714  100.825404.224   100.2
    5410      96    5429      96  5478.3   88.15  5502.4   91.08  5513.5      96
 5532.25      965551.864  102.195876.234  100.756483.904  116.33  7930.6  120.52
BR D #Mann= 5
  3281.5     .13    4955    .045 5123.03     .13    5429    .045 5532.25     .13
BR D Banks=4955,5123.03
BC Design=,, 0 ,, 0 ,,,,,,
BC HTab HWMax=129.55
BC Use User HTab Curves=0
BC User HTab FreeFlow(D)= 0

Type RM Length L Ch R = 1 ,346437. ,142,142,142
XS GIS Cut Line= 6
2104503.71592054474619.7396541682103287.99689528 474402.08884275
2101691.48401222473857.8527265042101468.89653087473850.437387004
2100649.98871988474164.5765224992100075.27694279473924.505152255
#Sta/Elev= 30
 3282.17  131.69 3481.43  129.97 3740.46  119.01 3780.31  112.32 3840.09  108.31
 3860.01  110.47 3939.72  107.05 3947.17  113.92  3959.2   116.9 4139.59  116.34
  4649.1   99.61 4971.68   96.22 5011.49    86.2    5054   95.44 5141.76   98.01
 5224.79   95.07 5312.61   98.13 5472.87   96.16 5495.38   90.86  5524.6   96.45
 5673.48   97.04 5851.61  105.76  6092.7  102.82 6433.27  111.65 6585.69  110.25
 6609.87  107.24 6641.99  116.51 6661.41     117 7197.26     114 7928.88     120
#Mann= 5 ,-1 , 0
 3282.17     .13       0 4971.68    .045       0    5054     .13       0
 5472.87    .045       0  5524.6     .13       0
#XS Ineff= 3 ,-1
 3282.17 4941.17  104.24 5156.17 5404.17  104.85 5553.17 7928.88  103.99
Permanent Ineff=
       F       F       F
Bank Sta=4971.68,5054
XS Rating Curve= 0 ,0
Exp/Cntr=0.5,0.3

Type RM Length L Ch R = 1 ,346295  ,2295,2295,2295
XS GIS Cut Line= 6
2104555.99942388474508.6956960832103308.33379686474286.455543831
2101697.00368619473738.5790149122101443.01174012473730.117417663
2100639.61538103474035.4114264992100149.37583552473830.626095978
#Sta/Elev= 30
 3177.35  129.61 3336.12  131.83 3534.58  121.83 3613.97  123.67 3693.36  111.29
 3792.59     107 3812.43  107.14 3835.95  116.84 4009.17  117.14 4605.72  100.84
 4761.87  100.76 4774.42   95.64 4882.41   94.49 4899.94    99.2 4977.56   95.06
 5001.79   86.53 5025.06   94.25  5047.9   95.48 5445.29   95.09 5472.25   91.62
 5485.05   95.55 5733.25   96.53 5884.57  103.08 6068.84  101.42  6426.5  110.54
 6527.89  107.19 6553.48     117 6730.23  118.09 6983.06  113.46  7793.4  118.25
#Mann= 5 ,-1 , 0
 3177.35     .13       0 4977.56    .045       0  5047.9     .13       0
 5445.29    .045       0 5485.05     .13       0
#XS Ineff= 3 ,-1
    4526 4766.35  104.24 5099.35 5230.35  104.85 5496.35    6183  103.99
Permanent Ineff=
       F       F       F
Bank Sta=4977.56,5047.9
XS Rating Curve= 0 ,0
Exp/Cntr=0.3,0.1

Type RM Length L Ch R = 1 ,344000.0,2000,2000,2000
BEGIN DESCRIPTION:
South River 172.0
END DESCRIPTION:
XS GIS Cut Line= 3
2104514.65438815471926.2418808682103111.80017347472511.957815744
2101904.66794198473082.133593156
#Sta/Elev= 23
  3479.8  110.44  3494.8  109.44  3524.8  108.83  3539.8   107.9  3554.8  104.72
  3569.8  102.11  3584.8  101.03  4274.8   98.24  4334.8  100.31  4364.8    98.9
  4454.8   99.45  4469.8  100.39  4484.8  100.56  4529.8   97.94  4946.1   96.49
  4950.6   87.49  5049.4   87.49  5053.9   96.49    5150   98.44    6065  102.53
    6080  103.32    6140  104.34    6335  110.01
#Mann= 3 , 1 , 0
  3479.8     .14       0  4946.1    .045       0  5053.9     .13       0
Bank Sta=4946.1,5053.9
XS Rating Curve= 0 ,0
Exp/Cntr=0.3,0.1

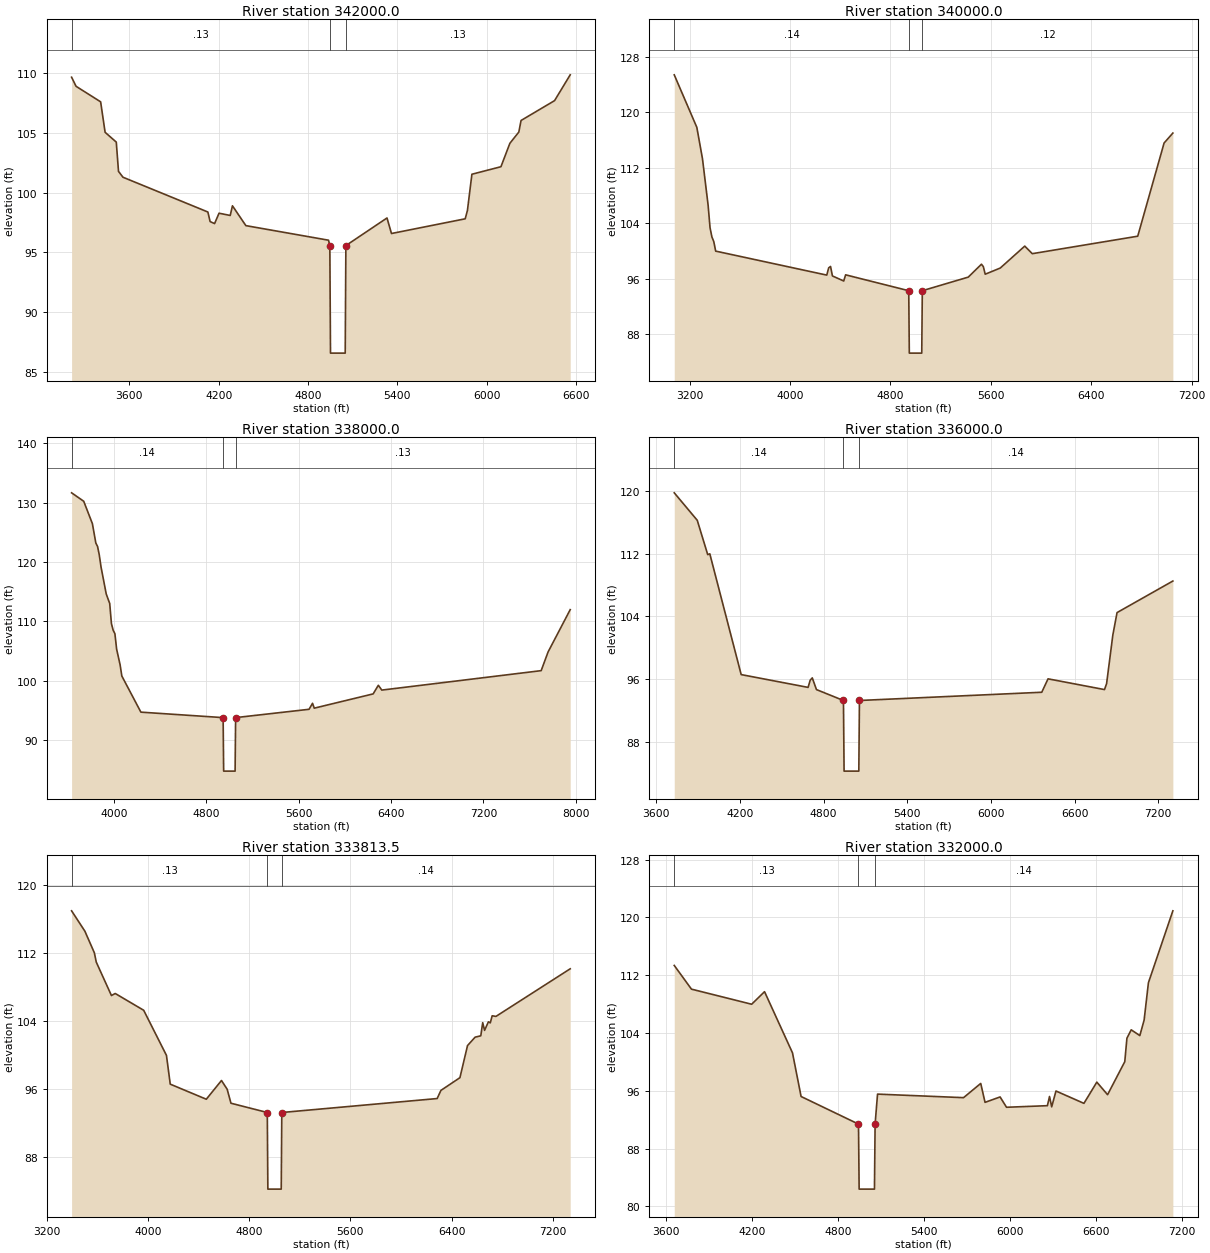
Type RM Length L Ch R = 1 ,342000.0,2000.02,2000.02,2000.02
BEGIN DESCRIPTION:
South River 171.0
END DESCRIPTION:
XS GIS Cut Line= 3
2104100.02018679471154.9140652442102343.72239078470821.210683932
2100799.12673987471039.972900581
#Sta/Elev= 30
  3212.3  109.66  3242.3   108.9  3407.3   107.6  3437.3  105.05  3512.3  104.23
  3527.3  101.78  3557.3  101.29  4127.3   98.38  4142.3   97.58  4172.3   97.41
  4202.3   98.28  4277.3   98.09  4292.3    98.9  4382.3   97.24  4937.3   96.02
  4946.1   95.57  4950.6   86.57  5049.4   86.57  5053.9   95.57    5330   97.88
    5360   96.58    5855   97.81    5870   98.51    5900  101.54    6095  102.17
    6155  104.13    6215  105.07    6230  106.04    6455   107.7    6560  109.86
#Mann= 3 , 1 , 0
  3212.3     .13       0  4946.1    .045       0  5053.9     .13       0
Bank Sta=4946.1,5053.9
XS Rating Curve= 0 ,0
Exp/Cntr=0.3,0.1

Type RM Length L Ch R = 1 ,340000.0,2000.02,2000.02,2000.02
BEGIN DESCRIPTION:
South River 170.0
END DESCRIPTION:
XS GIS Cut Line= 3
2104753.61680948 469761.689948142102969.84873512469046.052696812
2100931.68808308469264.844913765
#Sta/Elev= 28
    3078  125.37    3258  117.79    3303  113.25    3348  106.53    3363  103.33
    3378  101.99    3393  101.32    3408   99.95    4293   96.49    4308   97.53
    4323   97.74    4338   96.37    4428   95.64    4443   96.53  4945.9   94.24
  4950.4   85.24  5049.5   85.24    5054   94.24    5420    96.2    5525   98.06
    5540   97.72    5555   96.62    5675   97.51    5870  100.67    5930   99.58
    6770   102.1    6980  115.54  7049.8  116.97
#Mann= 3 , 1 , 0
    3078     .14       0  4945.9    .045       0    5054     .12       0
Bank Sta=4945.9,5054
XS Rating Curve= 0 ,0
Exp/Cntr=0.3,0.1

Type RM Length L Ch R = 1 ,338000.0,2000.02,2000.02,2000.02
BEGIN DESCRIPTION:
South River 169.0
END DESCRIPTION:
XS GIS Cut Line= 3
2104715.39642221467707.3991326552103411.87321402467298.074985101
2100998.56876076468997.302202839
#Sta/Elev= 29
  3633.7  131.64  3738.7  130.22  3813.7  126.46  3843.7  123.19  3858.7  122.61
  3873.7  121.16  3888.7  119.16  3933.7  114.62  3963.7  113.04  3978.7  109.64
  3993.7  108.53  4008.7  107.95  4023.7  105.34  4053.7  102.72  4068.7  100.83
  4233.7   94.75  4945.9   93.83  4950.4   84.83  5049.6   84.83  5054.1   93.83
    5690   95.23    5720   96.24    5735   95.42    6245   97.82    6290   99.27
    6320   98.46    7700  101.73    7760  104.88  7951.4  111.99
#Mann= 3 , 1 , 0
  3633.7     .14       0  4945.9    .045       0  5054.1     .13       0
Bank Sta=4945.9,5054.1
XS Rating Curve= 0 ,0
Exp/Cntr=0.3,0.1

Type RM Length L Ch R = 1 ,336000.0,2186.522,2186.522,2186.522
BEGIN DESCRIPTION:
South River 168.0
END DESCRIPTION:
XS GIS Cut Line= 3
2105384.24319942466465.2765466152104346.71268645465731.119107628
 2102393.5728959464506.536699318
#Sta/Elev= 20
    3729  119.74    3894  116.24    3969  111.87    3984  111.97    4209   96.58
    4689   94.95    4704   95.86    4719   96.16    4749   94.67  4942.6   93.28
  4947.1   84.28  5052.8   84.28  5057.3   93.28    6365   94.33    6410   96.04
    6815   94.67    6830   95.43    6875  101.65    6905  104.48  7305.3   108.5
#Mann= 3 , 1 , 0
    3729     .14       0  4942.6    .045       0  5057.3     .14       0
Bank Sta=4942.6,5057.3
XS Rating Curve= 0 ,0
Exp/Cntr=0.3,0.1

Type RM Length L Ch R = 1 ,333813.5,1813.518,1813.518,1813.518
BEGIN DESCRIPTION:
South River 167.0
END DESCRIPTION:
XS GIS Cut Line= 3
  2106339.722881464153.0031170732104724.95651908464191.223504348
 2102422.2431864463856.810115842
#Sta/Elev= 30
  3395.5  116.95  3500.5  114.56  3575.5  112.02  3590.5  110.93  3710.5     107
  3740.5  107.24  3965.5  105.27  4145.5   99.97  4175.5   96.59  4460.5   94.82
  4580.5   97.02  4625.5   95.99  4655.5   94.35  4942.7   93.26  4947.2   84.26
  5052.9   84.26  5057.4   93.26  6285.7    94.9  6315.7   95.86  6465.7   97.35
  6525.7  101.12  6585.7  102.11  6630.7  102.27  6645.7  103.81  6660.7  102.91
  6690.7  103.91  6705.7  103.79  6720.7  104.62  6750.7  104.55  7337.6  110.14
#Mann= 3 , 1 , 0
  3395.5     .13       0  4942.7    .045       0  5057.4     .14       0
Bank Sta=4942.7,5057.4
XS Rating Curve= 0 ,0
Exp/Cntr=0.3,0.1

Type RM Length L Ch R = 1 ,332000.0,1723.318,1723.318,1723.318
BEGIN DESCRIPTION:
South River 166.0
END DESCRIPTION:
XS GIS Cut Line= 3
2105489.34426438462060.5019144132104311.62233089462706.898464147
2102183.37076599462882.210240526
#Sta/Elev= 30
  3656.6  113.36  3776.6  110.08  4196.6  107.99  4286.6  109.73  4481.6  101.26
  4541.6   95.22  4942.1    91.4  4946.6    82.4  5053.5    82.4    5058    91.4
    5075   95.55    5675   95.06    5795   97.03    5825   94.41    5930   95.16
    5975   93.73    6260   93.95    6275   95.22    6290   93.79    6320   95.98
    6515   94.27    6605   97.21    6680   95.47    6800  100.04    6815  103.29
    6845  104.45    6905  103.65    6935   105.8    6965  110.97  7135.5  120.92
#Mann= 3 , 1 , 0
  3656.6     .13       0  4942.1    .045       0    5058     .14       0
Bank Sta=4942.1,5058
XS Rating Curve= 0 ,0
Exp/Cntr=0.3,0.1