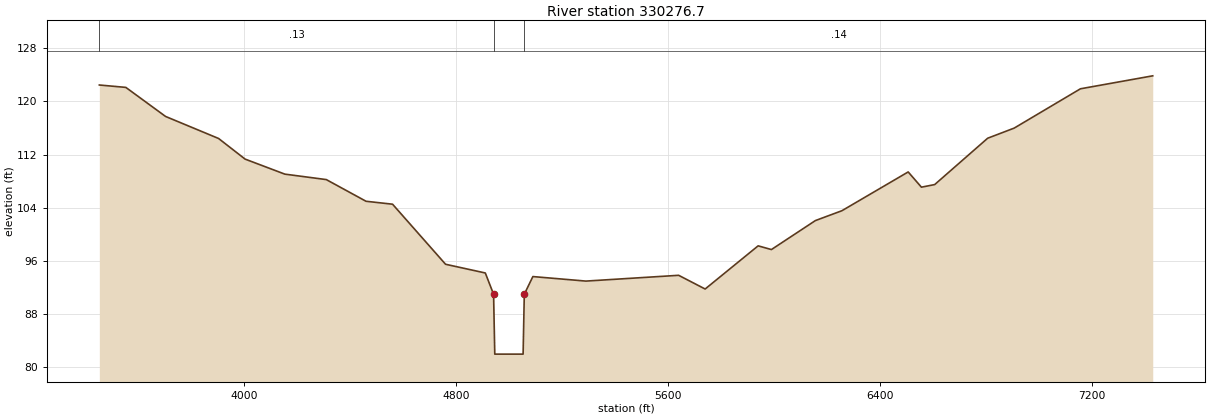
HEC-RAS study B4950SOUTHRIVERS.prj: B4950 SOUTH RIVER SR1851

--- B4950SOUTHRIVERS.g03 (geometry) --- (continued)

Type RM Length L Ch R = 1 ,330276.7,0,0,0
BEGIN DESCRIPTION:
South River T
END DESCRIPTION:
XS GIS Cut Line= 5
2105882.99825315462247.8138123862105319.18254018461671.197969718
  2104627.245529461312.4043341742103589.32501208461068.941867245
2102269.50163872461158.642776157
#Sta/Elev= 30
  3454.4  122.46  3554.4   122.1  3704.4  117.73  3904.4  114.42  4004.4  111.32
  4154.4  109.06  4310.8  108.24  4460.8  104.98  4560.8  104.54  4760.8   95.51
  4910.8    94.2    4942      91  4946.5      82  5053.4      82  5057.9      91
  5090.3   93.66  5290.3   92.98  5640.3   93.85  5740.3   91.79  5940.3   98.28
  5990.3   97.72  6156.4  102.08  6256.4  103.56  6506.4  109.39  6556.4   107.1
  6606.4  107.49  6806.4  114.46  6906.4  115.98  7156.4  121.89  7429.2  123.84
#Mann= 3 , 1 , 0
  3454.4     .13       0    4942    .045       0  5057.9     .14       0
Bank Sta=4942,5057.9
XS Rating Curve= 0 ,0
Exp/Cntr=0.3,0.1

Chan Stop Cuts=-1
Use User Specified Reach Order=0
Composite Channel Slope=5

--- B4950SOUTHRIVERS.g01 (geometry) ---

Geom Title=Duplicate Effective
Program Version=4.10

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
River Reach=South River     ,Reach - 1

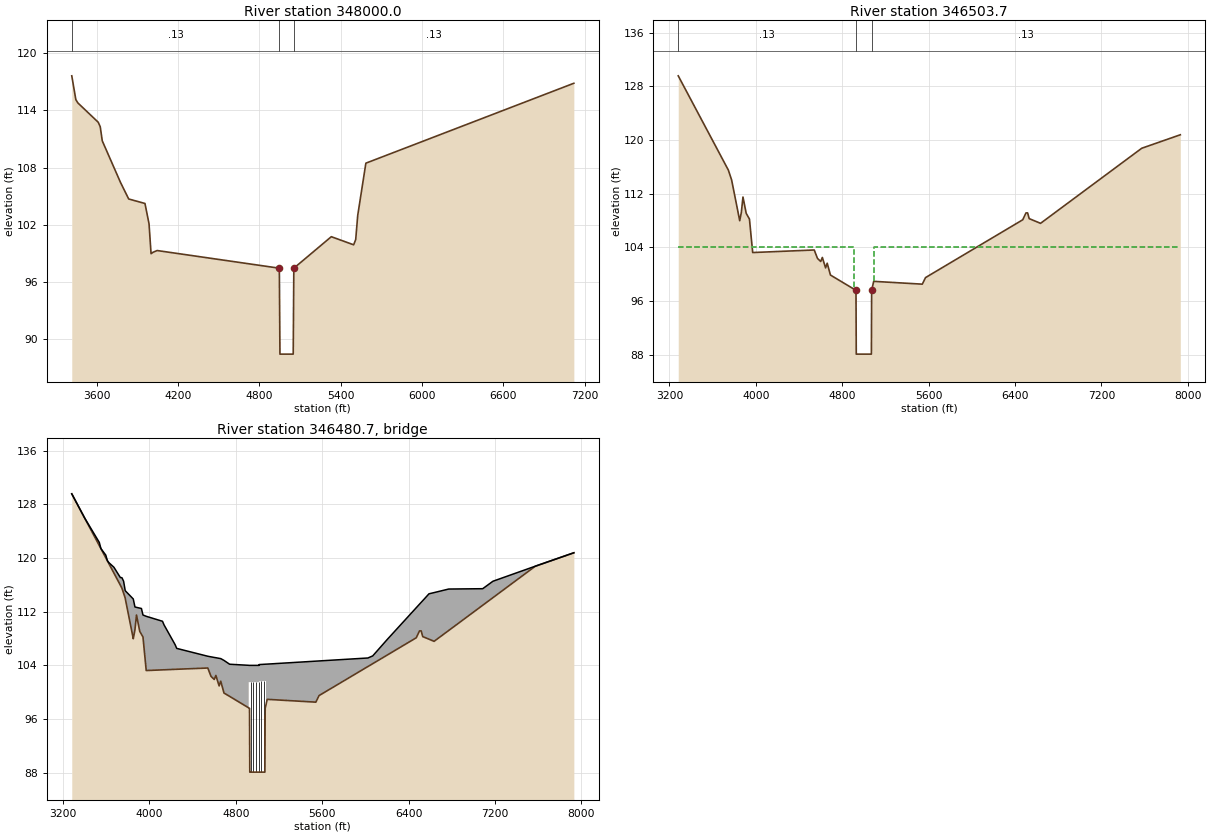
Type RM Length L Ch R = 1 ,348000.0,1496.315,1496.315,1496.315
BEGIN DESCRIPTION:
South River 174.0
END DESCRIPTION:
XS GIS Cut Line= 3
2103393.31302595475690.3500213972101868.18757233475259.475655482
2099861.54723967474577.328743501
#Sta/Elev= 23
  3415.2  117.61  3445.2  115.12  3460.2  114.77  3610.2  112.75  3625.2  112.28
  3640.2   110.8  3775.2  106.43  3835.2  104.71  3955.2  104.24  3985.2  102.11
  4000.2   98.98  4015.2   99.13  4045.2   99.31  4946.6   97.46  4951.1   88.46
    5049   88.46  5053.5   97.46    5330  100.76    5495   99.91    5510  100.46
    5525     103    5585  108.46  7119.4  116.83
#Mann= 3 , 1 , 0
  3415.2     .13       0  4946.6    .045       0  5053.5     .13       0
Bank Sta=4946.6,5053.5
XS Rating Curve= 0 ,0
Exp/Cntr=0.5,0.3

Type RM Length L Ch R = 1 ,346503.7,46.0005,46.0005,46.0005
BEGIN DESCRIPTION:
Upstream Section of Bridge/Culvert/Weir
END DESCRIPTION:
XS GIS Cut Line= 6
2104482.58406319474683.1198154492103265.73173321474465.217607514
2101670.56556989473921.3120962892101450.83334341473913.992022117
2100630.51503138474228.9352133382100051.89916845473987.232764243
#Sta/Elev= 30
  3281.5  129.55  3745.9   115.5  3775.9  114.04  3850.9  107.97  3865.9  109.21
  3880.9   111.5  3910.9  109.07  3940.9  108.22  3970.9  103.23  4540.9  103.61
  4570.9  102.36  4600.9   101.9  4615.9   102.5  4645.9  100.94  4660.9  101.64
  4690.9   99.88  4927.5    97.6    4930    88.1    5070    88.1  5072.5    97.6
  5091.5   98.94  5541.5   98.52  5571.5    99.5  6471.5  108.11  6501.5  109.13
  6516.5  109.14  6531.5  108.28  6636.5  107.58  7573.2  118.76  7930.6  120.77
#Mann= 3 , 1 , 0
  3281.5     .13       0  4927.5    .045       0  5072.5     .13       0
#XS Ineff= 2 , 0
       0    4905     104    5095       0     104
Permanent Ineff=
       F       F
Bank Sta=4927.5,5072.5
XS Rating Curve= 0 ,0
Exp/Cntr=0.5,0.3

Type RM Length L Ch R = 3 ,346480.7,,,
BEGIN DESCRIPTION:
Faircloth Rd-TOR
Structure ID: HLS-0492
Approximate Survey Structure
END DESCRIPTION:
Bridge Culvert--1,0,-1,-1, 0
Deck Dist Width WeirC Skew NumUp NumDn MinLoCord MaxHiCord MaxSubmerge Is_Ogee
10,26,2.6,0, 55, 55, , , 0.95, 0, 1,1,,
  3281.5  3401.5  3536.5  3551.5  3596.5  3611.5  3626.5  3671.5  3731.5  3745.9
  3761.5  3776.5  3850.9  3866.5  3880.9  3910.9  3926.5  3940.9  3970.9  4121.5
  4136.5  4238.3  4253.3  4540.9  4570.9  4600.9  4615.9  4645.9  4660.9  4690.9
  4743.3 4919.91    4920    4925  5016.1  5016.4 5079.89    5080  5091.5  5541.5
  5571.5  6023.2  6068.2  6204.4  6471.5  6501.5  6516.5  6531.5  6589.2  6636.5
  6771.7  7086.7  7181.2  7573.2  7930.6
  129.55  125.93  122.31  121.39  120.42  119.58  119.28  118.62  117.08  117.06
  116.53  115.12  113.89   112.7  112.64  112.53  112.47   111.5  111.31  110.57
  110.01  107.09  106.53  105.36  105.27  105.18  105.14  105.05  105.01  104.74
  104.17  104.01  104.01     104     104  104.12  104.18  104.18  104.19  104.63
  104.66   105.1  105.41  107.89  112.59  113.12  113.38  113.64  114.66  114.84
  115.37  115.42  116.53  118.77  120.77
  129.55  125.92  121.84  121.38  120.02  119.57  119.11  117.75  115.94   115.5
  114.74  113.99  107.97   109.3   111.5  109.07  108.63  108.22  103.23  103.33
  103.34  103.41  103.42  103.61  102.36   101.9   102.5  100.94  101.64   99.88
   99.38   97.67  101.51   101.5   101.5  101.62  101.68   98.13   98.94   98.52
    99.5  103.82  104.25  105.55  108.11  109.13  109.14  108.28   107.9  107.58
  109.19  112.95  114.08  118.76  120.77
  3281.5  3401.5  3536.5  3551.5  3596.5  3611.5  3626.5  3671.5  3731.5  3745.9
  3761.5  3776.5  3850.9  3866.5  3880.9  3910.9  3926.5  3940.9  3970.9  4121.5
  4136.5  4238.3  4253.3  4540.9  4570.9  4600.9  4615.9  4645.9  4660.9  4690.9
  4743.3 4919.91    4920    4925  5016.1  5016.4 5079.89    5080  5091.5  5541.5
  5571.5  6023.2  6068.2  6204.4  6471.5  6501.5  6516.5  6531.5  6589.2  6636.5
  6771.7  7086.7  7181.2  7573.2  7930.6
  129.55  125.93  122.31  121.39  120.42  119.58  119.28  118.62  117.08  117.06
  116.53  115.12  113.89   112.7  112.64  112.53  112.47   111.5  111.31  110.57
  110.01  107.09  106.53  105.36  105.27  105.18  105.14  105.05  105.01  104.74
  104.17  104.01  104.01     104     104  104.12  104.18  104.18  104.19  104.63
  104.66   105.1  105.41  107.89  112.59  113.12  113.38  113.64  114.66  114.84
  115.37  115.42  116.53  118.77  120.77
   129.3  125.67  121.59  121.13  119.77  119.32  118.86   117.5  115.69  115.25
  114.49  113.74  107.72  109.05  111.25  108.82  108.38  107.97  102.98  103.08
  103.09  103.16  103.17  103.36  102.11  101.65  102.25  100.69  101.39   99.63
   99.13   97.42  101.26  101.25  101.25  101.37  101.43   97.88   98.69   98.27
   99.25  103.57     104   105.3  107.86  108.88  108.89  108.03  107.65  107.33
  108.94   112.7  113.83  118.51  120.52
Pier Skew, UpSta & Num, DnSta & Num=  ,4937.5, 2 ,4937.5, 2 , 0 , 0 , 0 ,,
       1       1
    87.1   102.5
       1       1
   86.85  102.25
Pier Skew, UpSta & Num, DnSta & Num=  ,4962.5, 2 ,4962.5, 2 , 0 , 0 , 0 ,,
       1       1
    87.1   102.5
       1       1
   86.85  102.25
Pier Skew, UpSta & Num, DnSta & Num=  ,4987.5, 2 ,4987.5, 2 , 0 , 0 , 0 ,,
       1       1
    87.1   102.5
       1       1
   86.85  102.25
Pier Skew, UpSta & Num, DnSta & Num=  ,5012.5, 2 ,5012.5, 2 , 0 , 0 , 0 ,,
       1       1
    87.1   102.5
       1       1
   86.85  102.25
Pier Skew, UpSta & Num, DnSta & Num=  ,5037.5, 2 ,5037.5, 2 , 0 , 0 , 0 ,,
       1       1
    87.1  102.64
       1       1
   86.85  102.39
Pier Skew, UpSta & Num, DnSta & Num=  ,5062.5, 2 ,5062.5, 2 , 0 , 0 , 0 ,,
       1       1
    87.1  102.66
       1       1
   86.85  102.41
Abutment Skew #Up #Dn= , 2 , 2
  4919.8    4925
  101.51   97.62
  4919.8    4925
  101.26   97.37
Abutment Skew #Up #Dn= , 2 , 2
    5075 5080.09
   97.78  101.68
    5075 5080.09
   97.53  101.43
BR Coef= 1 , 1 , 0 ,1.25, 0 ,,,0.8,0,2,0,
WSPro=,,,, 1 ,,,, 0 ,,,, 0 ,,,,-1 ,-1 ,-1 , 0 , 0 , 0 , 0 , 0
BR U #Sta/Elev= 72
  3281.5  129.55  3296.5   129.1  3326.5  128.19  3386.5  126.37  3401.5  125.92
  3536.5  121.84  3551.5  121.38  3596.5  120.02  3611.5  119.57  3626.5  119.11
  3671.5  117.75  3731.5  115.94  3745.9   115.5  3746.5  115.47  3761.5  114.74
  3775.9  114.04  3776.5  113.99  3850.9  107.97  3851.5  108.02  3865.9  109.21
  3866.5   109.3  3880.9   111.5  3910.9  109.07  3926.5  108.63  3940.9  108.22
  3941.5  108.12  3970.9  103.23  4121.5  103.33  4136.5  103.34  4238.3  103.41
  4253.3  103.42  4518.3  103.59  4540.9  103.61  4570.9  102.36  4600.9   101.9
  4615.9   102.5  4645.9  100.94  4660.9  101.64  4668.3  101.21  4690.9   99.88
  4743.3   99.38 4919.91   97.67    4920   97.67    4925   97.62  4927.5    97.6
    4930    88.1  4930.3    88.1    5000    88.1  5016.1    88.1  5016.4    88.1
    5070    88.1  5072.5    97.6    5075   97.78 5079.89   98.12    5080   98.13
  5091.5   98.94  5541.5   98.52  5571.5    99.5  6023.2  103.82  6068.2  104.25
  6204.4  105.55  6471.5  108.11  6501.5  109.13  6516.5  109.14  6531.5  108.28
  6589.2   107.9  6636.5  107.58  6771.7  109.19  7086.7  112.95  7181.2  114.08
  7573.2  118.76  7930.6  120.77
BR U #Mann= 3
  3281.5     .13  4927.5    .045  5072.5     .13
BR U Banks=4927.5,5072.5
BR D #Sta/Elev= 72
  3281.5   129.3  3296.5  128.85  3326.5  127.94  3386.5  126.12  3401.5  125.67
  3536.5  121.59  3551.5  121.13  3596.5  119.77  3611.5  119.32  3626.5  118.86
  3671.5   117.5  3731.5  115.69  3745.9  115.25  3746.5  115.22  3761.5  114.49
  3775.9  113.79  3776.5  113.74  3850.9  107.72  3851.5  107.77  3865.9  108.96
  3866.5  109.05  3880.9  111.25  3910.9  108.82  3926.5  108.38  3940.9  107.97
  3941.5  107.87  3970.9  102.98  4121.5  103.08  4136.5  103.09  4238.3  103.16
  4253.3  103.17  4518.3  103.34  4540.9  103.36  4570.9  102.11  4600.9  101.65
  4615.9  102.25  4645.9  100.69  4660.9  101.39  4668.3  100.96  4690.9   99.63
  4743.3   99.13 4919.91   97.42    4920   97.42    4925   97.37  4927.5   97.35
    4930   87.85  4930.3   87.85    5000   87.85  5016.1   87.85  5016.4   87.85
    5070   87.85  5072.5   97.35    5075   97.53 5079.89   97.87    5080   97.88
  5091.5   98.69  5541.5   98.27  5571.5   99.25  6023.2  103.57  6068.2     104
  6204.4   105.3  6471.5  107.86  6501.5  108.88  6516.5  108.89  6531.5  108.03
  6589.2  107.65  6636.5  107.33  6771.7  108.94  7086.7   112.7  7181.2  113.83
  7573.2  118.51  7930.6  120.52
BR D #Mann= 3
  3281.5     .13  4927.5    .045  5072.5     .13
BR D Banks=4927.5,5072.5
BC Design=,, 0 ,, 0 ,,,,,,
BC HTab HWMax=129.55
BC Use User HTab Curves=0
BC User HTab FreeFlow(D)= 0