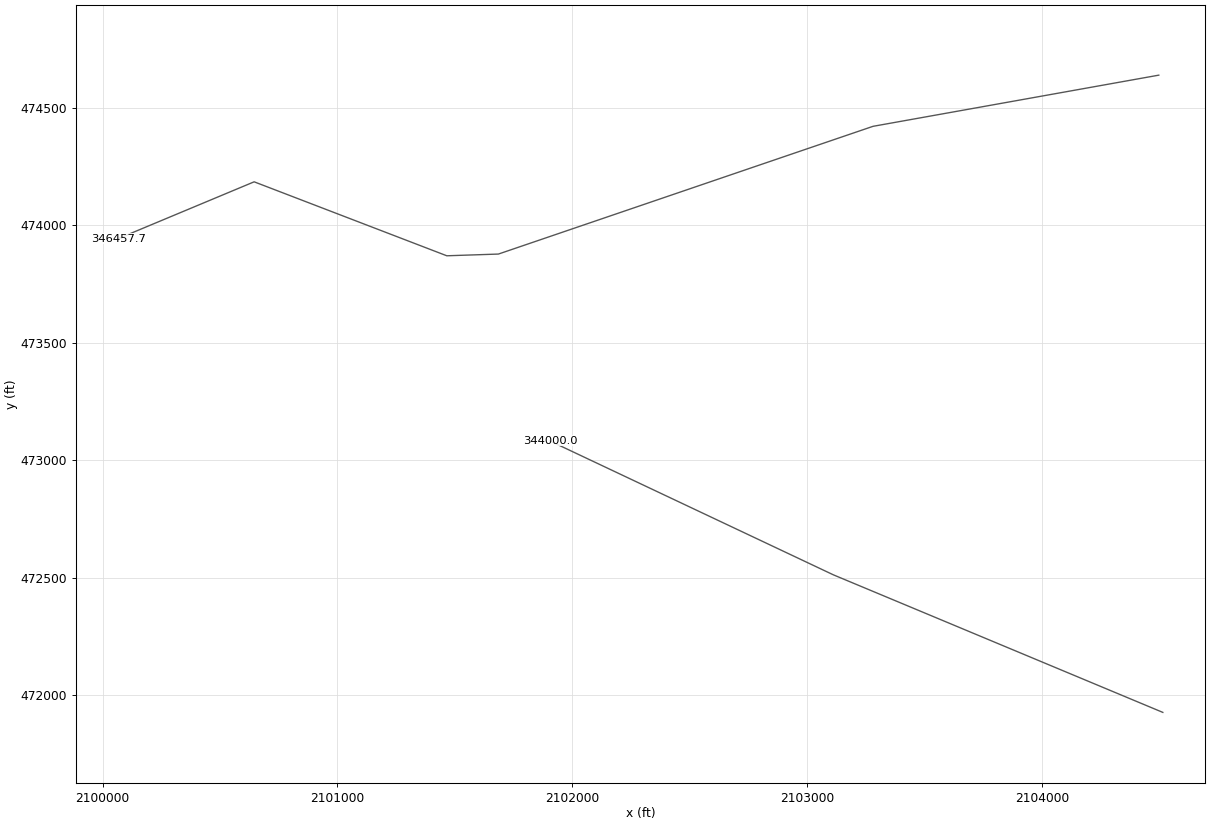
HEC-RAS study B4950SOUTHRIVERS.prj: B4950 SOUTH RIVER SR1851

--- B4950SOUTHRIVERS.g01 (geometry) --- (continued)

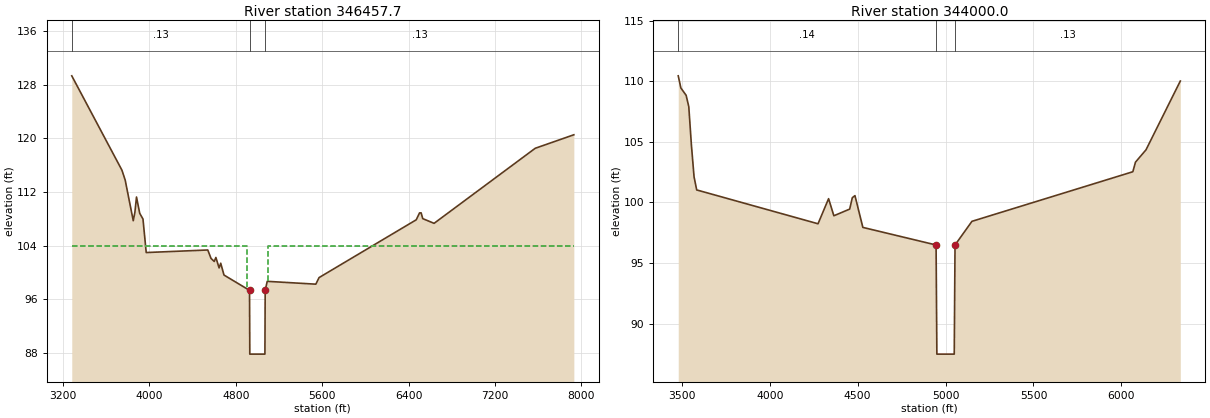
Type RM Length L Ch R = 1 ,346457.7,2457.725,2457.725,2457.725
BEGIN DESCRIPTION:
Downstream Section of Bridge/Culvert/Weir
END DESCRIPTION:
XS GIS Cut Line= 6
2104497.52421458474639.6093745712103280.67188459474421.717166737
2101685.50572127473877.811655513 2101465.7734948473870.491581341
2100645.45518277474185.4347725622100066.83931984473943.732323467
#Sta/Elev= 30
  3281.5   129.3  3745.9  115.25  3775.9  113.79  3850.9  107.72  3865.9  108.96
  3880.9  111.25  3910.9  108.82  3940.9  107.97  3970.9  102.98  4540.9  103.36
  4570.9  102.11  4600.9  101.65  4615.9  102.25  4645.9  100.69  4660.9  101.39
  4690.9   99.63  4927.5   97.35    4930   87.85    5070   87.85  5072.5   97.35
  5091.5   98.69  5541.5   98.27  5571.5   99.25  6471.5  107.86  6501.5  108.88
  6516.5  108.89  6531.5  108.03  6636.5  107.33  7573.2  118.51  7930.6  120.52
#Mann= 3 , 1 , 0
  3281.5     .13       0  4927.5    .045       0  5072.5     .13       0
#XS Ineff= 2 , 0
       0    4905     104    5095       0     104
Permanent Ineff=
       F       F
Bank Sta=4927.5,5072.5
XS Rating Curve= 0 ,0
Exp/Cntr=0.5,0.3

Type RM Length L Ch R = 1 ,344000.0,2000.02,2000.02,2000.02
BEGIN DESCRIPTION:
South River 172.0
END DESCRIPTION:
XS GIS Cut Line= 3
2104514.65438815471926.2418808682103111.80017347472511.957815744
2101904.66794198473082.133593156
#Sta/Elev= 23
  3479.8  110.44  3494.8  109.44  3524.8  108.83  3539.8   107.9  3554.8  104.72
  3569.8  102.11  3584.8  101.03  4274.8   98.24  4334.8  100.31  4364.8    98.9
  4454.8   99.45  4469.8  100.39  4484.8  100.56  4529.8   97.94  4946.1   96.49
  4950.6   87.49  5049.4   87.49  5053.9   96.49    5150   98.44    6065  102.53
    6080  103.32    6140  104.34    6335  110.01
#Mann= 3 , 1 , 0
  3479.8     .14       0  4946.1    .045       0  5053.9     .13       0
Bank Sta=4946.1,5053.9
XS Rating Curve= 0 ,0
Exp/Cntr=0.3,0.1

--- B4950SOUTHRIVERS.g02 (geometry) ---

Geom Title=Corrected Effective
Program Version=4.10

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
River Reach=South River     ,Reach - 1

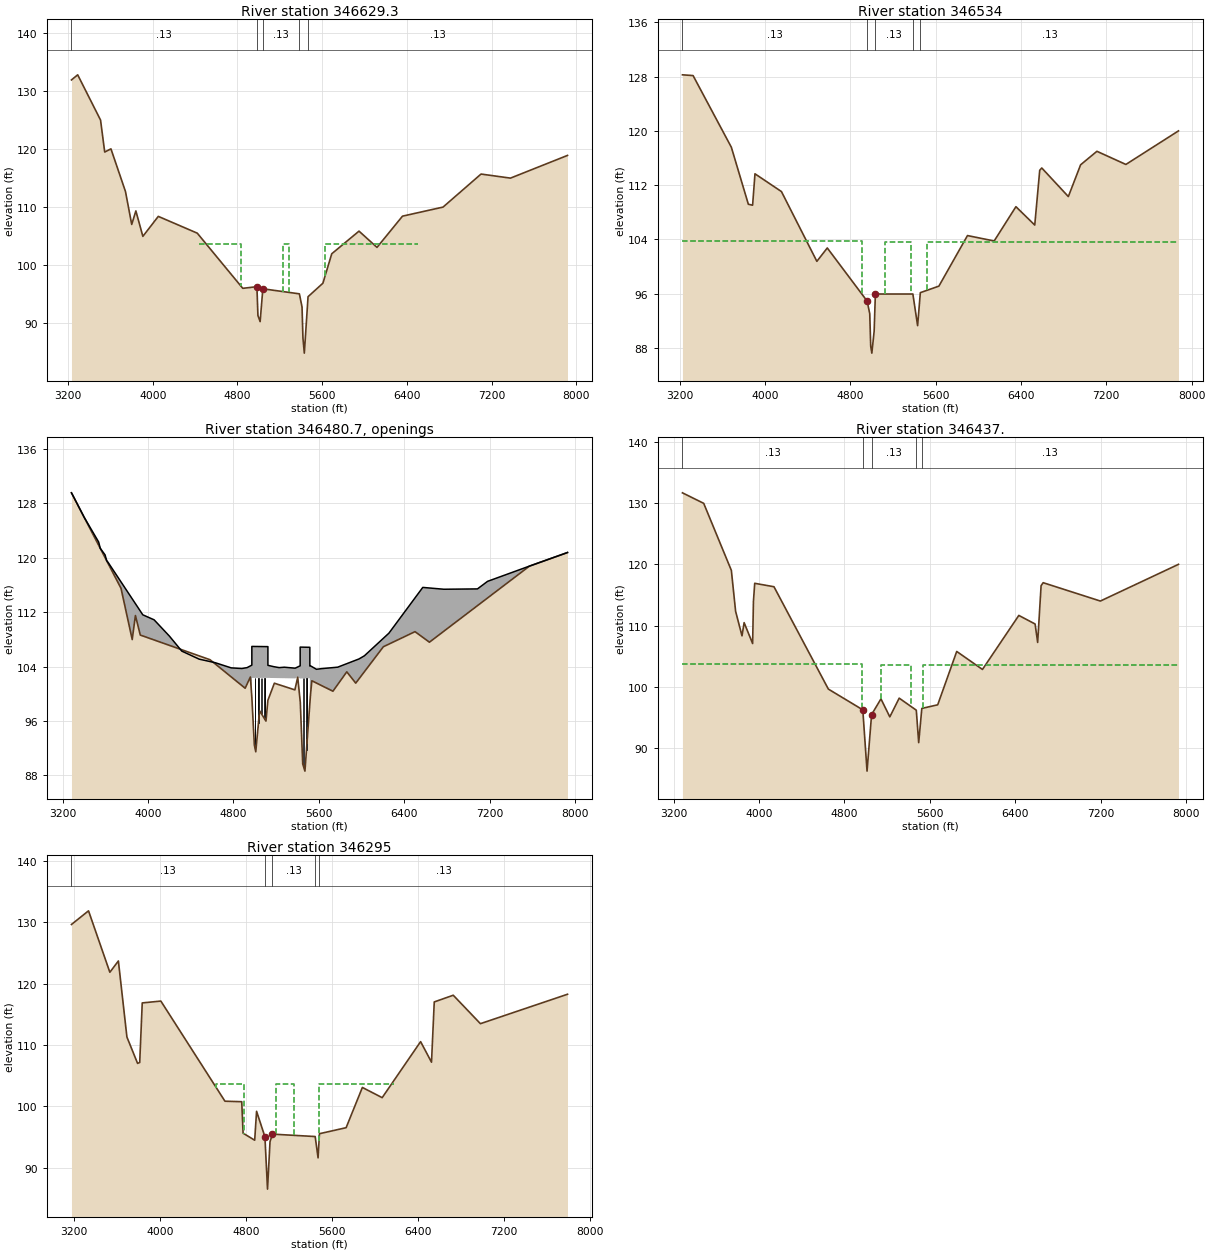
Type RM Length L Ch R = 1 ,346629.3,95.3,95.3,95.3
XS GIS Cut Line= 6
2104463.28293052474801.5572039192103232.83001086474580.755152091
2101653.82726339474040.8211925772101468.35519338474034.642399162
2100631.11474186474359.234597757 2100005.6451923474097.960185915
#Sta/Elev= 30
  3233.1  131.91 3291.93  132.79 3507.65     125 3546.87  119.49  3605.7  120.04
 3742.98  112.69 3801.81  107.02 3841.03  109.35    3907  104.97  4052.7  108.41
 4420.55  105.52 4850.02   96.02  4983.5    96.3 4993.15   91.34 5013.96   90.29
 5039.58   95.94 5384.53   95.07 5409.47    92.8 5418.07   87.46  5431.1   84.86
 5466.27   94.58 5606.46    96.9 5689.93  101.97 5947.24  105.87 6117.06  103.07
 6357.73  108.45  6740.4  110.01 7099.06   115.7 7376.92     115 7915.21  118.91
#Mann= 5 ,-1 , 0
  3233.1     .13       0  4983.5    .045       0 5039.58     .13       0
 5384.53    .045       0 5466.27     .13       0
#XS Ineff= 3 ,-1
    4440  4829.1   103.7  5228.1  5282.1   103.6  5627.1    6500   103.6
Permanent Ineff=
       F       F       F
Bank Sta=4983.5,5039.58
XS Rating Curve= 0 ,0
Exp/Cntr=0.5,0.3

Type RM Length L Ch R = 1 ,346534  ,97,97,97
XS GIS Cut Line= 6
2104491.80879211474715.4894626742103273.82336721474497.345870078
2101680.00372019473953.7711698412101463.12685737473946.546118662
2100641.39818588474262.2935186622100058.87802544474018.960015833
#Sta/Elev= 30
 3224.77  128.27 3324.47  128.16 3683.39  117.59 3842.91  109.18 3882.79  109.04
 3905.08  113.67 4153.27  111.05 4485.41  100.76  4583.1  102.73 4957.25   94.89
 4981.33   93.03 4990.45   88.22 5000.98   87.22 5022.72   90.48 5034.11   95.94
 5385.76   95.94 5430.23   91.27 5455.81   96.14 5629.71    97.1 5898.02  104.56
  6148.2  103.76 6352.21  108.82  6528.8  106.11 6575.41  114.19 6594.59  114.53
 6843.83  110.31 6958.81     115  7111.9  116.99 7383.39  115.05  7876.6     120
#Mann= 5 ,-1 , 0
 3224.77     .13       0 4957.25    .045       0 5034.11     .13       0
 5385.76    .045       0 5455.81     .13       0
#XS Ineff= 3 ,-1
 3224.77 4907.77   103.7 5124.77 5363.77   103.6 5522.77  7876.6   103.6
Permanent Ineff=
       F       F       F
Bank Sta=4957.25,5034.11
XS Rating Curve= 0 ,0
Exp/Cntr=0.5,0.3

Type RM Length L Ch R = 4 ,346480.7,,,
BEGIN DESCRIPTION:
Faircloth Rd-TOR
Structure ID: HLS-0492
Approximate Survey Structure
END DESCRIPTION:
Bridge Culvert--1,0,-1,-1, 0
Deck Dist Width WeirC Skew NumUp NumDn MinLoCord MaxHiCord MaxSubmerge Is_Ogee
38,25.667,2.6,0, 44, 44, , , 0.98, 0, 1,1,,
  3281.5  3296.5  3326.5  3386.5  3401.5  3536.5  3551.5  3596.5  3611.5  3626.5
3950.1524056.0784199.5344315.7634478.8444628.5924778.1984877.7744927.871    4972
    49725122.7495122.7495177.3285227.8365277.4485377.973    5425    54255515.749
5515.7495524.7815577.5795626.8545776.8195976.7686026.9246256.8846574.193  6771.7
  7086.7  7181.2  7573.2  7930.6
  129.55  129.11   128.2  126.38  125.93  122.31  121.39  120.42  119.58  119.28
 111.609 110.874 108.477 106.268 105.086 104.567 103.808 103.711 103.846  104.21
  106.96  106.93  104.18 103.984 103.843 103.905  103.76  104.11  106.86 106.831
  104.08 104.081 103.598 103.696  103.91 105.122 105.583 108.912 115.641  115.37
  115.42  116.53  118.77  120.77
                                                                                
                                                                                
  102.33  102.33                                                  102.24  102.28
                                                                                
                                
  3281.5  3296.5  3326.5  3386.5  3401.5  3536.5  3551.5  3596.5  3611.5  3626.5
3950.1524056.0784199.5344315.7634478.8444628.5924778.1984877.7744927.871    4972
    49725122.7495122.7495177.3285227.8365277.4485377.973    5430    54305520.749
5520.7495524.7815577.5795626.8545776.8195976.7686026.9246256.8846574.193  6771.7
  7086.7  7181.2  7573.2  7930.6
  129.55  129.11   128.2  126.38  125.93  122.31  121.39  120.42  119.58  119.28
 111.609 110.874 108.477 106.268 105.086 104.567 103.808 103.711 103.846  104.21
  106.96  106.93  104.18 103.984 103.843 103.905  103.76  104.11  106.86 106.831
  104.08 104.081 103.598 103.696  103.91 105.122 105.583 108.912 115.641  115.37
  115.42  116.53  118.77  120.77
                                                                                
                                                                                
  102.31  102.33                                                  102.21   102.3
                                                                                
                                
Pier Skew, UpSta & Num, DnSta & Num=  ,5000.67, 2 ,5000.67, 2 , 0 , 0 , 0 ,,
    1.17    1.17
    87.1     103
    1.17    1.17
   86.85     103
Pier Skew, UpSta & Num, DnSta & Num=  ,5003.84, 2 ,5003.84, 2 , 0 , 0 , 0 ,,
    1.17    1.17
    87.1     103
    1.17    1.17
   86.85     103
Pier Skew, UpSta & Num, DnSta & Num=  ,5030.75, 2 ,5030.75, 2 , 0 , 0 , 0 ,,
    1.17    1.17
    87.1     103
    1.17    1.17
   86.85     103
Pier Skew, UpSta & Num, DnSta & Num=  ,5033.92, 2 ,5033.92, 2 , 0 , 0 , 0 ,,
    1.17    1.17
    87.1     103
    1.17    1.17
   86.85     103
Pier Skew, UpSta & Num, DnSta & Num=  ,5060.84, 2 ,5060.84, 2 , 0 , 0 , 0 ,,
    1.17    1.17
    87.1     103
    1.17    1.17
   86.85     103
Pier Skew, UpSta & Num, DnSta & Num=  ,5064.01, 2 ,5064.01, 2 , 0 , 0 , 0 ,,
    1.17    1.17
    87.1     103
    1.17    1.17
   86.85     103
Pier Skew, UpSta & Num, DnSta & Num=  ,5090.92, 2 ,5090.92, 2 , 0 , 0 , 0 ,,
    1.17    1.17
    87.1     103
    1.17    1.17
   86.85     103
Pier Skew, UpSta & Num, DnSta & Num=  ,5094.09, 2 ,5094.09, 2 , 0 , 0 , 0 ,,
    1.17    1.17
    87.1     103
    1.17    1.17
   86.85     103
Pier Skew, UpSta & Num, DnSta & Num=  ,5453.75, 2 ,5453.75, 2 , 0 , 0 , 0 ,,
    1.17    1.17
    87.1     103
    1.17    1.17
   86.85     103
Pier Skew, UpSta & Num, DnSta & Num=  ,5456.92, 2 ,5456.92, 2 , 0 , 0 , 0 ,,
    1.17    1.17
    87.1     103
    1.17    1.17
   86.85     103
Pier Skew, UpSta & Num, DnSta & Num=  ,5483.84, 2 ,5483.84, 2 , 0 , 0 , 0 ,,
    1.17    1.17
    87.1  102.66
    1.17    1.17
   86.85  102.41
Pier Skew, UpSta & Num, DnSta & Num=  ,5487.01, 2 ,5487.01, 2 , 0 , 0 , 0 ,,
    1.17    1.17
    87.1  102.66
    1.17    1.17
   86.85  102.41
Abutment Skew #Up #Dn= , 3 , 3
    4972    4973    4973
  102.33  102.33      90
    4972    4973    4973
  102.33  102.33      90
Abutment Skew #Up #Dn= , 3 , 3
 5121.75 5121.75 5122.75
   97.78  102.33  102.33
 5121.75 5121.75 5122.75
   97.53  102.33  102.33
Abutment Skew #Up #Dn= , 3 , 3
    5425    5426    5426
  102.24  102.24      90
    5430    5431    5431
  102.31  102.31      90
Abutment Skew #Up #Dn= , 3 , 3
 5514.75 5514.75 5515.75
      90  102.28  102.28
 5519.75 5519.75 5520.75
      90   102.3   102.3
BR Coef= 1 , 1 , 0 ,0.9, 0 ,,,0.8,0,1.2,0,
WSPro=,,,, 1 ,,,, 0 ,,,, 0 ,,,,-1 ,-1 ,-1 , 0 , 0 , 0 , 0 , 0
BC Mult= 3 ,3224.77,5200,3282.17,5200
BC Mult= 3 ,5200,7876.6,5200,7928.88
BR U #Sta/Elev= 30
  3281.5  129.55  3745.9   115.5  3850.9  107.97  3880.9   111.5  3926.5  108.63
  4580.6     105 4909.39  100.81 4958.38  102.46    4972    99.5  4995.8   92.44
  5008.8   91.46 5044.55    97.5 5104.45   95.98  5122.6   99.04 5183.22  101.55
 5375.44  100.57 5402.05  102.43  5426.2   98.75    5449   89.68  5469.7   88.62
 5521.12   99.72 5534.38  101.91 5732.03  100.37 5861.96  103.22 5945.94  101.56
 6204.72  106.91  6501.5  109.13  6636.5  107.58  7573.2  118.76  7930.6  120.77
BR U #Mann= 5
  3281.5     .13    4972    .045  5122.6     .13  5426.2    .045 5521.12     .13
BR U Banks=4972,5122.6
BR D #Sta/Elev= 30
  3281.5   129.3  3745.9  115.25  3850.9  107.72  3880.9  111.25  3941.5  107.87
4650.614  105.924667.044   104.14804.544   99.634877.404   99.474925.774  101.72
    4972   98.39    4982   94.76    4990   94.76  4995.7   92.39  5008.6   92.29
  5044.4   97.66  5104.2    95.9  5122.9   99.465184.994  101.275337.834  101.09
  5430.7   98.65  5478.3   88.15  5502.4   91.08  5511.7   94.12  5520.3   99.69
5549.934  102.235718.544  100.435876.234  100.756483.904  116.33  7930.6  120.52
BR D #Mann= 5
  3281.5     .13    4972    .045  5122.9     .13  5430.7    .045  5520.3     .13
BR D Banks=4972,5122.9
BC Design=,, 0 ,, 0 ,,,,,,
BC HTab HWMax=129.55
BC Use User HTab Curves=0
BC User HTab FreeFlow(D)= 0

Type RM Length L Ch R = 1 ,346437. ,142,142,142
XS GIS Cut Line= 6
2104503.71592054474619.7396541682103287.99689528 474402.08884275
2101691.48401222473857.8527265042101468.89653087473850.437387004
2100649.98871988474164.5765224992100075.27694279473924.505152255
#Sta/Elev= 30
 3282.17  131.69 3481.43  129.97 3740.46  119.01 3780.31  112.32 3840.09  108.31
 3860.01  110.47 3939.72  107.05 3947.17  113.92  3959.2   116.9 4139.59  116.34
  4649.1   99.61 4971.68   96.22 5011.49    86.2    5054   95.44 5141.76   98.01
 5224.79   95.07 5312.61   98.13 5472.87   96.16 5495.38   90.86  5524.6   96.45
 5673.48   97.04 5851.61  105.76  6092.7  102.82 6433.27  111.65 6585.69  110.25
 6609.87  107.24 6641.99  116.51 6661.41     117 7197.26     114 7928.88     120
#Mann= 5 ,-1 , 0
 3282.17     .13       0 4971.68    .045       0    5054     .13       0
 5472.87    .045       0  5524.6     .13       0
#XS Ineff= 3 ,-1
 3282.17 4961.17   103.7 5141.17 5420.17   103.6 5539.17 7928.88   103.6
Permanent Ineff=
       F       F       F
Bank Sta=4971.68,5054
XS Rating Curve= 0 ,0
Exp/Cntr=0.5,0.3

Type RM Length L Ch R = 1 ,346295  ,2295,2295,2295
XS GIS Cut Line= 6
2104555.99942388474508.6956960832103308.33379686474286.455543831
2101697.00368619473738.5790149122101443.01174012473730.117417663
2100639.61538103474035.4114264992100149.37583552473830.626095978
#Sta/Elev= 30
 3177.35  129.61 3336.12  131.83 3534.58  121.83 3613.97  123.67 3693.36  111.29
 3792.59     107 3812.43  107.14 3835.95  116.84 4009.17  117.14 4605.72  100.84
 4761.87  100.76 4774.42   95.64 4882.41   94.49 4899.94    99.2 4977.56   95.06
 5001.79   86.53 5025.06   94.25  5047.9   95.48 5445.29   95.09 5472.25   91.62
 5485.05   95.55 5733.25   96.53 5884.57  103.08 6068.84  101.42  6426.5  110.54
 6527.89  107.19 6553.48     117 6730.23  118.09 6983.06  113.46  7793.4  118.25
#Mann= 5 ,-1 , 0
 3177.35     .13       0 4977.56    .045       0  5047.9     .13       0
 5445.29    .045       0 5485.05     .13       0
#XS Ineff= 3 ,-1
    4526 4787.35   103.7 5084.35 5246.35   103.6 5481.35    6183   103.6
Permanent Ineff=
       F       F       F
Bank Sta=4977.56,5047.9
XS Rating Curve= 0 ,0
Exp/Cntr=0.3,0.1